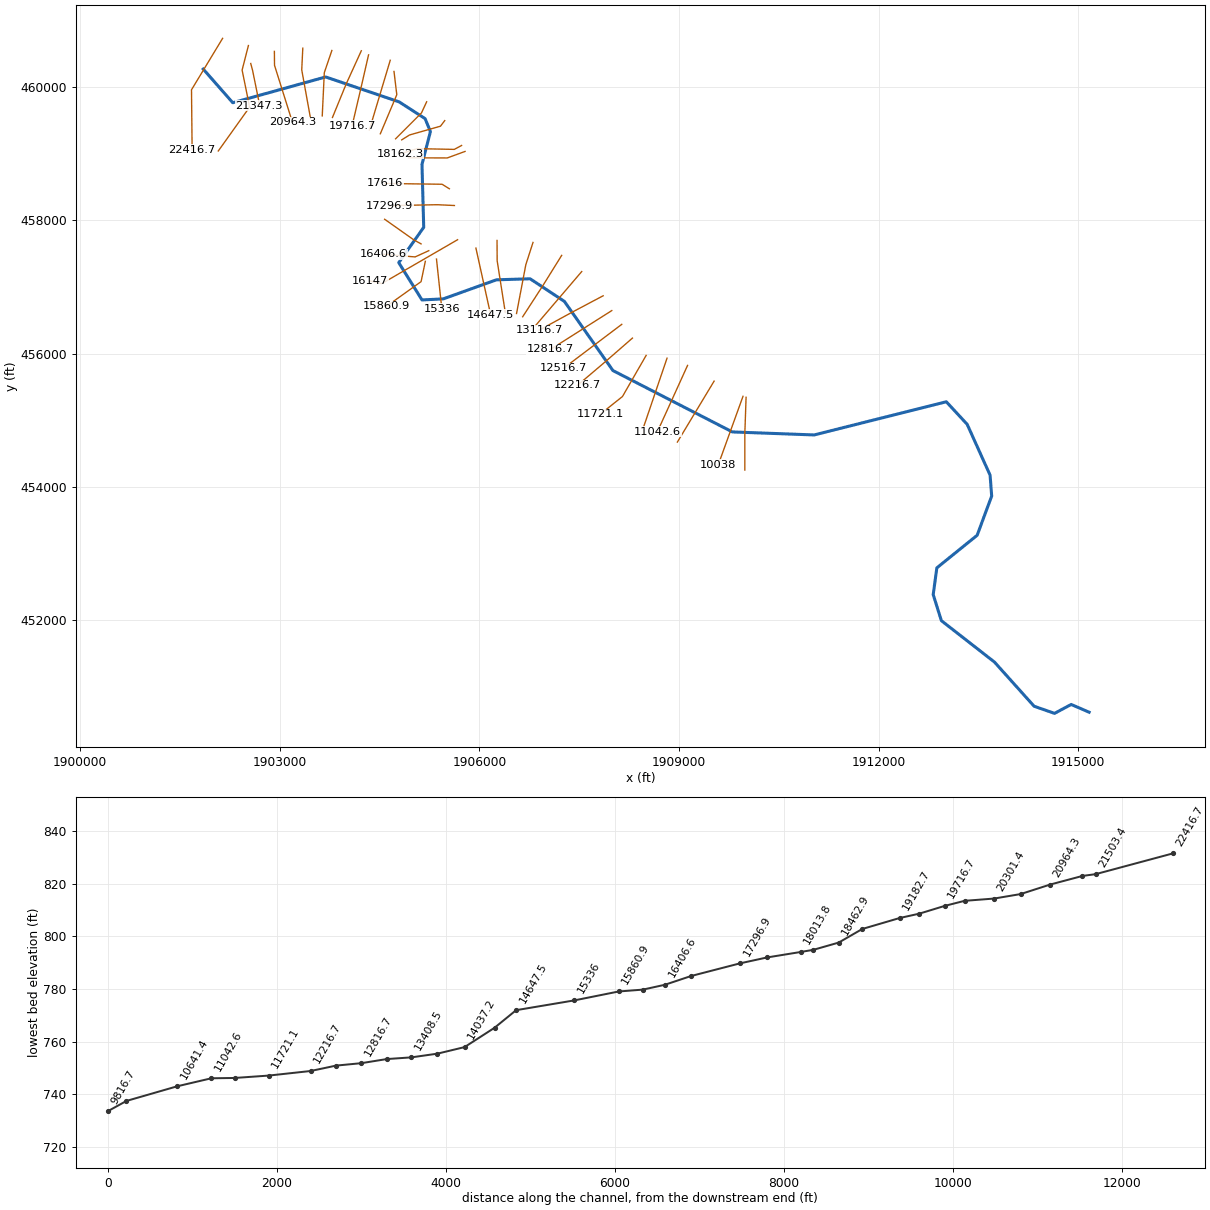
--- BellsCreek.prj (project) ---

Proj Title=BellsCreek
Current Plan=p01
Default Exp/Contr=0,0
English Units
Geom File=g01
Flow File=f01
Plan File=p01
BEGIN DESCRIPTION:
END DESCRIPTION:
DSS Export Rating Curves= 0
DSS Export Rating Curve Sorted= 0
DSS Export Volume Flow Curves= 0
DXF OffsetX= 0
DXF OffsetY= 0
DXF ScaleX= 0
DXF ScaleY= 0

--- BellsCreek.p01 (plan) ---

Plan Title=Floodplain
Program Version=4.00
Geom File=g01
Flow File=f01
K Sum by GR=0
Std Step Tol=0.01
Critical Tol=0.01
Num of Std Step Trials=20
Max Error Tol=0.3
Flow Tol Ratio=0.001
Split Flow NTrial=30
Split Flow Tol=0.02
Split Flow Ratio=0.02
Log Output Level=0
Friction Slope Method=1
Unsteady Friction Slope Method=2
Unsteady Bridges Friction Slope Method=1
Global Log Level=0
CheckData=False
Run HTab=0
Run UNet=0
Run PostProcess=0
UNET Theta=0
UNET Theta Warmup=0
UNET ZTol=0
UNET ZSATol=0
UNET MxIter=0
UNET MaxInSteps=0
UNET DtIC=0
UNET DtMin=0
UNET MaxCRTS=0
UNET WFStab=0
UNET SFStab=0
UNET WFX=0
UNET SFX=0
UNET DSS MLevel=0
UNET DZMax Abort=0
UNET Convert EG Bridges=0
UNET Use Existing IB Tables=0
UNET Froude Limit=0
UNET Froude Power=0
Write IC File=0
Echo Input=False
Echo Output=False
Write Detailed=0

--- BellsCreek.f01 (steady flow) ---

Flow Title=NFF Regression Equation
Program Version=4.00
Number of Profiles=1
Profile Names=P100yr
River Rch & RM=BellsCreek,Main      ,22416.7
1619.935
River Rch & RM=BellsCreek,Main      ,21503.4
2918.126
River Rch & RM=BellsCreek,Main      ,15860.9
3118.582
River Rch & RM=BellsCreek,Main      ,6870.5
3409.488
River Rch & RM=BellsCreek,Main      ,6225.9
4704.480
River Rch & RM=BellsCreek,Main      ,106.5
4795.265
Boundary for River Rch & Prof#=BellsCreek,Main      ,1
Up Type=0
Dn Type=3
Dn Slope=0.00657

--- BellsCreek.g01 (geometry) ---

Geom Title=USGS 3m DEM
Program Version=4.10

River Reach=BellsCreek      ,Main
Reach XY= 30
     1901849.124      460271.631     1902292.977      459766.422
     1903688.811      460153.575     1904794.713      459778.574
     1905183.525      459527.434     1905263.463      459332.394
     1905136.727      458841.075     1905162.769      457894.894
     1904787.573      457364.646     1905136.727      456804.616
     1905456.172      456820.241     1906254.783      457106.699
     1906761.727      457122.324     1907277.352      456782.046
     1908006.519      455743.852     1909801.658      454821.977
     1911030.825      454776.838     1913016.936      455275.102
     1913330.344        454936.6     1913674.922      454172.672
     1913698.862      453859.489     1913480.477      453269.894
     1912874.574       452780.31     1912819.947      452378.928
     1912942.633      451987.473     1913740.894       451365.38
      1914336.38      450702.186     1914643.746       450594.99
     1914893.806      450729.005     1915163.521      450612.391

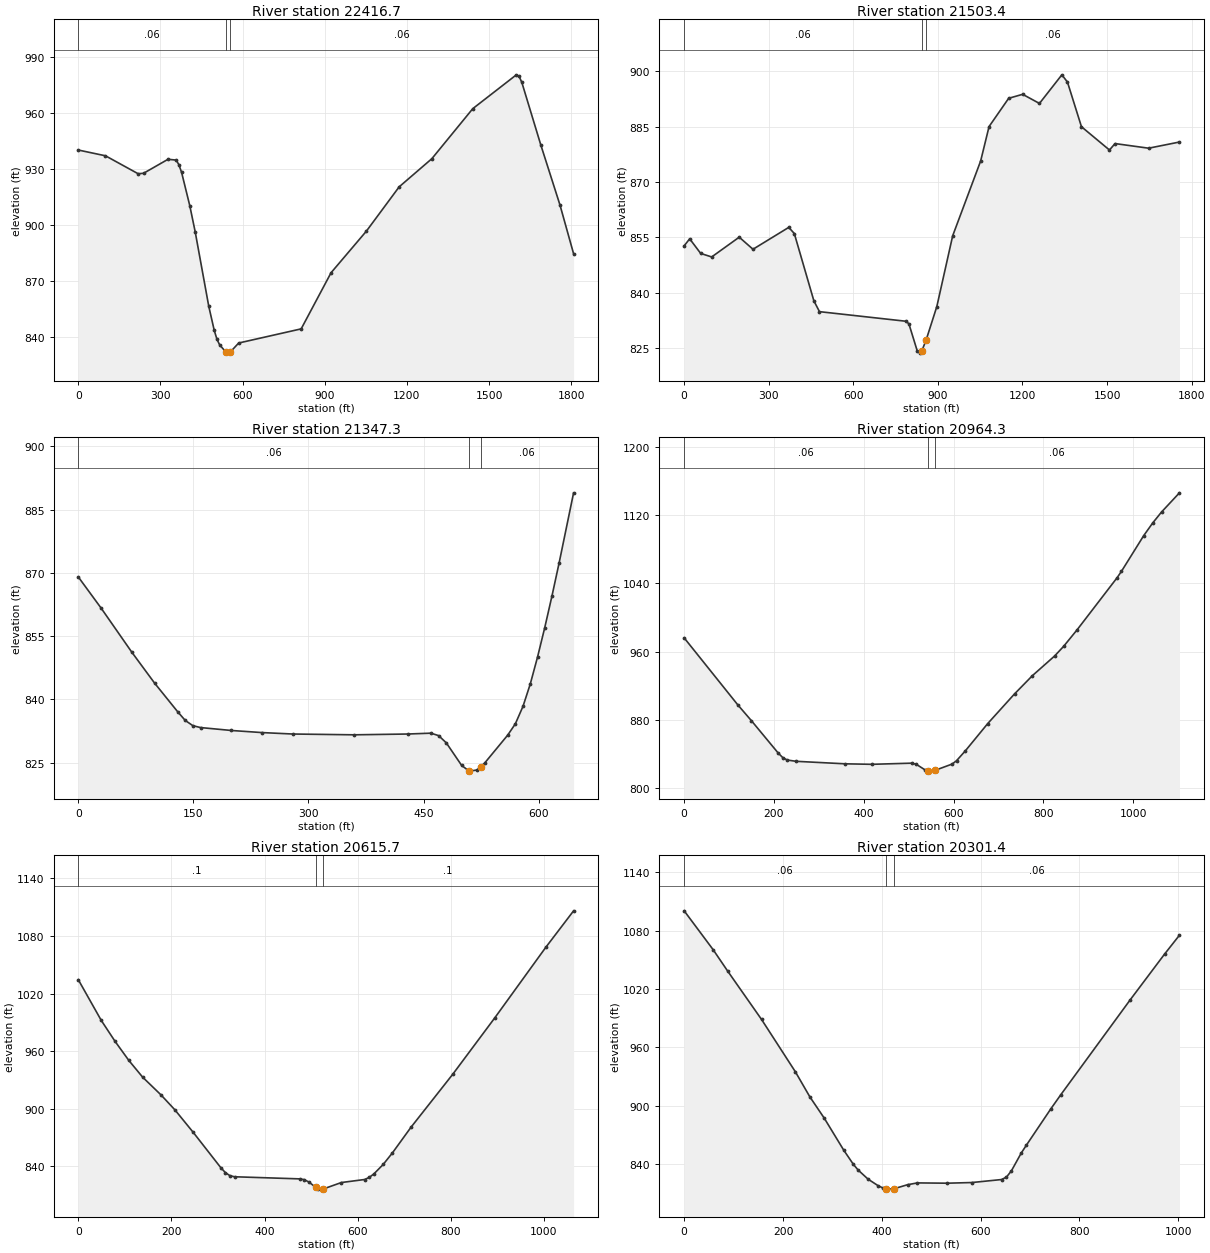
Type RM Length L Ch R = 1 ,22416.7 ,892.4,913.2,932.3
XS GIS Cut Line= 4
     1902140.399      460733.556     1901857.679      460266.453
     1901672.748      459960.914     1901682.041       459055.45
#Sta/Elev= 30
       0  940.26    99.3  937.17   218.4  927.58   238.2  927.81   327.6   935.3
   357.4  934.88   367.3  932.41   377.2   928.3     407  910.54   426.9  896.47
   476.5  856.58   496.4  843.76   506.3     839   516.2  835.99   538.5  832.25
     546  831.58   553.5  831.93   585.7  836.99   813.9  844.56     923   874.6
  1052.4  896.92  1171.8  920.57  1291.2  935.64  1440.5  962.39  1599.7   980.5
  1609.6  979.69  1619.6  976.49  1689.2  942.88  1758.9  910.89  1808.7  884.77
#Mann= 3 , 0 , 0
       0     .06       0   538.5    .045       0   553.5     .06       0
Bank Sta=538.5,553.5
XS Rating Curve= 0 ,0
Exp/Cntr=0.3,0.1

Type RM Length L Ch R = 1 ,21503.4 ,156.1,156.1,156.1
XS GIS Cut Line= 5
     1902528.059      460625.771     1902433.508      460256.885
      1902536.04      459751.819     1902542.717      459696.032
      1902075.12      459041.483
#Sta/Elev= 30
       0  852.72    19.5  854.62    58.6  850.66    97.6  849.71   195.3  855.06
   244.1  851.79     371  857.71   390.7  856.04   460.1  837.83   479.9  834.91
   787.2  832.31   797.1  831.62   826.8  824.27   836.7  823.69   843.4  824.38
   858.4  827.27   896.2   836.3   952.4  855.43  1051.7  875.69  1081.5  884.99
    1151  892.63  1200.6  893.71  1260.2  891.24  1339.7  898.98  1359.5  897.03
  1409.2  884.94  1508.5  878.64  1528.4  880.38  1647.5  879.13  1756.8   880.8
#Mann= 3 , 0 , 0
       0     .06       0   843.4    .045       0   858.4     .06       0
Bank Sta=843.4,858.4
XS Rating Curve= 0 ,0
Exp/Cntr=0.3,0.1

Type RM Length L Ch R = 1 ,21347.3 ,380.6,383,385.3
XS GIS Cut Line= 4
      1902563.31      460355.737     1902591.244      460249.985
     1902685.025      459789.065     1902685.025      459723.219
#Sta/Elev= 30
       0  869.05    29.8  861.65    69.6  851.25    99.4  843.89   129.4  837.12
   139.4  835.03   149.4  833.78   159.4  833.34   199.4  832.65   239.5  832.15
   279.5  831.81   359.6  831.62   429.6  831.81   459.6  832.01   469.7  831.43
   479.7  829.71   499.7  824.36   509.5  823.01   519.7  823.27   524.5  824.07
   529.7  824.93   559.7  831.54   569.7  834.23   579.7  838.39   589.2  843.71
   598.6  850.05     608  857.03   617.4  864.52   626.8  872.43   645.6     889
#Mann= 3 , 0 , 0
       0     .06       0   509.5    .045       0   524.5     .06       0
Bank Sta=509.5,524.5
XS Rating Curve= 0 ,0
Exp/Cntr=0.3,0.1

Type RM Length L Ch R = 1 ,20964.3 ,351.5,348.6,345.8
XS GIS Cut Line= 3
     1902918.478      460537.312     1902920.473      460327.803
     1903188.932      459475.436
#Sta/Elev= 30
       0   976.1   119.7  897.33   149.7  878.97   209.5   840.9   219.4   835.7
   229.4  832.76   249.2  831.25   358.5   828.3     418  827.72   507.4  829.07
   517.3  827.64   537.2  820.94   543.1  820.21   547.1  819.72   558.1  820.49
   596.8  828.02   606.7  831.96   626.6  843.72   676.2  875.58   735.8  910.32
   775.5   931.7   825.1  954.85     845  966.05   874.8  985.31   964.2 1046.64
   974.1  1054.3  1023.7 1096.22  1043.6 1110.97  1063.4  1123.9  1103.2 1146.36
#Mann= 3 , 0 , 0
       0     .06       0   543.1    .045       0   558.1     .06       0
Bank Sta=543.1,558.1
XS Rating Curve= 0 ,0
Exp/Cntr=0.3,0.1

Type RM Length L Ch R = 1 ,20615.7 ,319.4,314.3,309.1
XS GIS Cut Line= 3
     1903345.477        460585.2     1903329.515      460259.962
     1903461.146      459533.754
#Sta/Elev= 30
       0  1034.4    49.3  991.97    78.9  970.17   108.5  950.26   138.2   932.8
   177.6  914.32   207.2  898.88   246.7  875.36   305.9  838.57   315.8  833.36
   325.6  830.12   335.6     829   475.2   826.8   485.2     826   495.2  823.53
   510.2  817.85   515.1  816.26   525.1  816.11   525.2  816.12     565  822.99
   614.9  826.14   624.8  828.31   634.8  831.98   654.8  841.84   674.7  853.93
   714.6  880.67   804.4  935.98   894.1   994.4  1003.8 1068.03  1063.7  1106.2
#Mann= 3 , 0 , 0
       0      .1       0   510.2    .045       0   525.2      .1       0
Bank Sta=510.2,525.2
XS Rating Curve= 0 ,0
Exp/Cntr=0.3,0.1

Type RM Length L Ch R = 1 ,20301.4 ,357.2,349.4,341.7
XS GIS Cut Line= 3
     1903782.454      460551.279      1903668.72       460218.06
     1903637.722      459568.575
#Sta/Elev= 30
       0 1100.21    58.7 1060.24      88 1038.34   156.5  988.71     225  934.94
   254.3   909.2   283.6  887.18   322.8  854.51   342.3  839.92   352.1  833.98
   372.1  824.68   392.1  818.04   402.1  815.61   409.2  814.75   412.1   814.4
   424.2  814.74   452.1  818.94   472.1  820.79   532.2  820.49   582.2  821.17
   642.2  824.24   652.2  826.74   662.2  833.16   682.2  851.52   692.2  859.28
   742.2     897   762.2  911.36   902.3 1008.59   972.3 1055.86  1002.3 1075.17
#Mann= 3 , 0 , 0
       0     .06       0   409.2    .045       0   424.2     .06       0
Bank Sta=409.2,424.2
XS Rating Curve= 0 ,0
Exp/Cntr=0.3,0.1

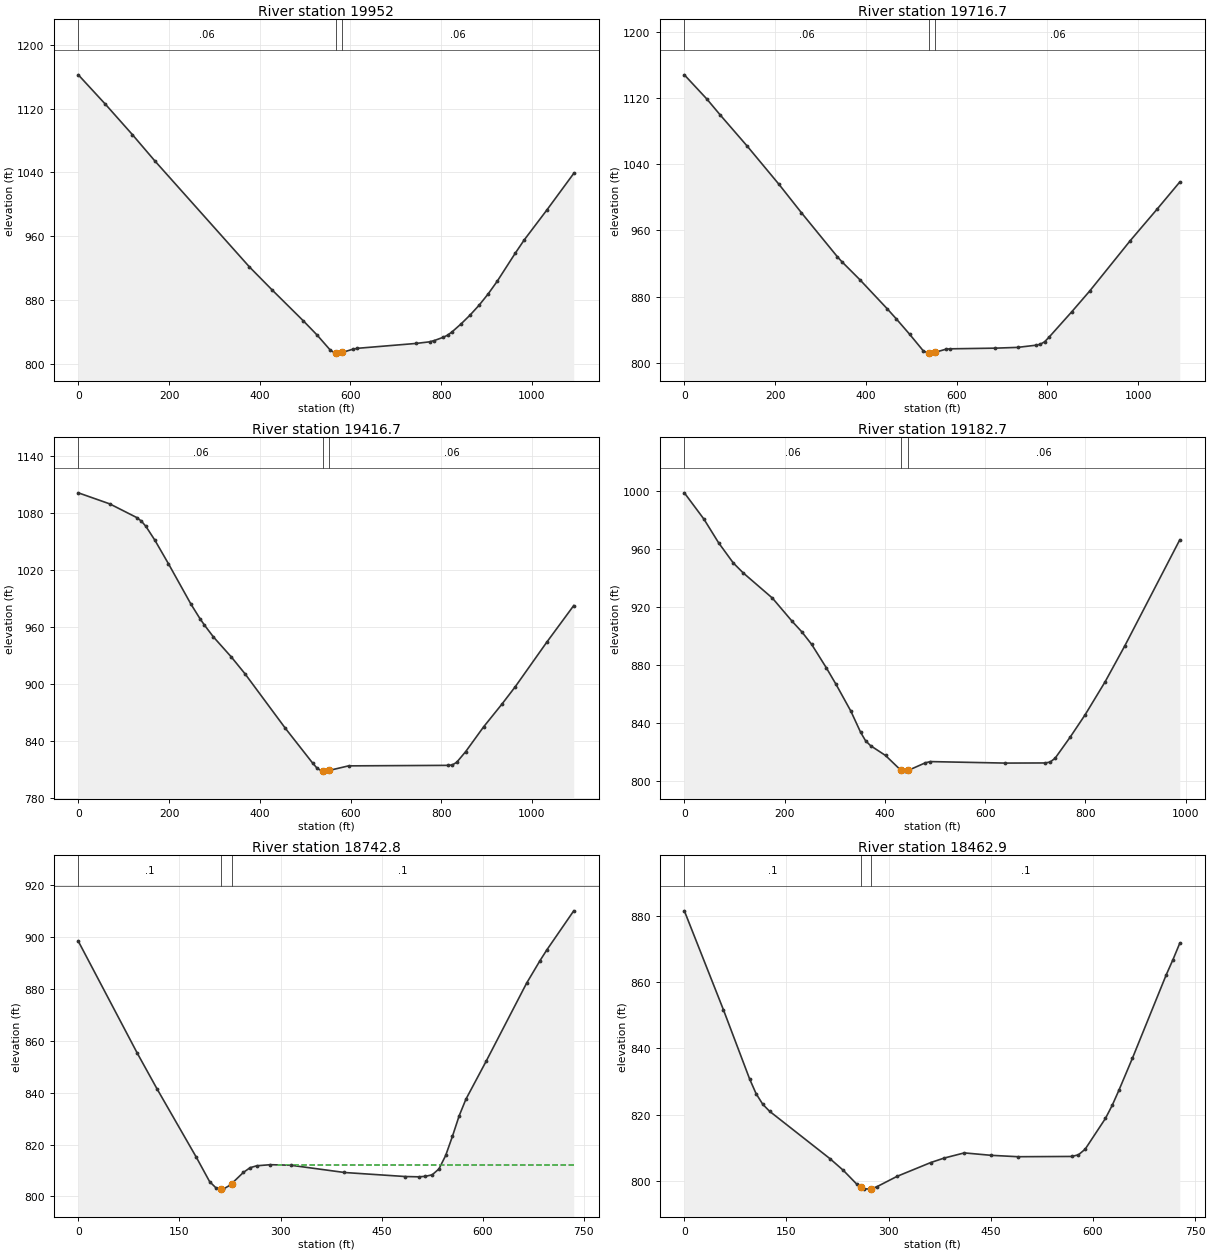
Type RM Length L Ch R = 1 ,19952   ,231.7,235.3,238.9
XS GIS Cut Line= 3
     1904225.104      460547.011     1903998.548      460050.329
     1903791.096      459544.741
#Sta/Elev= 30
       0  1162.2    59.6 1125.46   119.1 1087.38   168.7  1054.4   377.2  921.61
   426.8  893.01   496.3  853.91   526.1  836.45   555.8  817.18   565.8  813.82
   567.4  813.77   575.7  813.53   582.4  814.42   605.5  818.48   615.5  819.56
   744.6  825.66   774.4  827.69   784.4   829.2   804.3   833.3   814.2  836.01
   824.1  840.17     844  850.15   863.9  861.25   883.8  873.61   903.6  887.62
   923.5  903.45   963.2   938.5   983.1  955.26  1032.8  992.59  1092.4 1038.69
#Mann= 3 , 0 , 0
       0     .06       0   567.4    .045       0   582.4     .06       0
Bank Sta=567.4,582.4
XS Rating Curve= 0 ,0
Exp/Cntr=0.3,0.1

Type RM Length L Ch R = 1 ,19716.7 ,301.4,300,298.6
XS GIS Cut Line= 3
      1904333.72      460485.202     1904211.471      459953.066
     1904086.721        459421.5
#Sta/Elev= 30
       0 1147.84    49.6 1118.63    79.4 1099.15     139 1061.44   208.5  1015.6
   258.1  981.21   337.5  927.92   347.4  921.96   387.2  900.15   446.7  865.46
   466.6  853.38   496.4  834.52   526.1  814.75   536.1  811.75   538.5  811.71
     546   811.6   553.5  812.69   575.8  816.21   585.7   816.8     685   817.6
   734.6  818.54   774.3  821.12   784.3  822.22   794.2  825.38   804.1  830.99
   853.8  861.47   893.5  886.65   982.8  947.45  1042.4  985.79    1092 1018.33
#Mann= 3 , 0 , 0
       0     .06       0   538.5    .045       0   553.5     .06       0
Bank Sta=538.5,553.5
XS Rating Curve= 0 ,0
Exp/Cntr=0.3,0.1

Type RM Length L Ch R = 1 ,19416.7 ,236.3,233.8,231.4
XS GIS Cut Line= 3
     1904659.566      460404.264     1904502.674       459881.29
     1904345.783      459358.317
#Sta/Elev= 30
       0 1101.45    69.5 1089.78     129 1075.39     139 1071.66   148.9 1066.22
   168.8 1051.58   198.6 1026.92   248.2   984.4     268  969.19     278  962.31
   297.8  949.84   337.5  928.62   367.3  911.14   456.6  853.57   516.2  817.31
   526.2  811.78   536.1  808.86   538.5  808.81     546  808.65   553.5  809.45
   595.6  814.18     814  814.72     824   815.1   833.9  817.87   853.8  829.16
   893.4  855.27   933.2  878.84     963  897.38  1032.4  944.21    1092  982.86
#Mann= 3 , 0 , 0
       0     .06       0   538.5    .045       0   553.5     .06       0
Bank Sta=538.5,553.5
XS Rating Curve= 0 ,0
Exp/Cntr=0.3,0.1

Type RM Length L Ch R = 1 ,19182.7 ,448.8,440,431.3
XS GIS Cut Line= 3
     1904716.266      460236.018     1904758.168      459886.836
     1904510.798       459300.17
#Sta/Elev= 30
       0  999.07    39.1  980.92    68.4  964.57    97.7  950.65   117.2  943.88
   175.8  926.38   214.9  910.47   234.5  903.08     254  894.47   283.3  878.28
   302.8  866.79   332.2  848.39   351.7  833.77   361.6  827.92   371.6  824.54
   401.4  817.77   431.7  807.69   441.2  806.98   446.7  807.49     481  812.75
     491  813.56   640.2  812.53   719.8  812.62   729.7  813.23   739.7  815.88
   769.5  830.31   799.4  845.77   839.2  868.49   878.9  893.55   988.4  966.63
#Mann= 3 , 0 , 0
       0     .06       0   431.7    .045       0   446.7     .06       0
Bank Sta=431.7,446.7
XS Rating Curve= 0 ,0
Exp/Cntr=0.3,0.1

Type RM Length L Ch R = 1 ,18742.8 ,291.4,279.9,268.3
XS GIS Cut Line= 3
     1905207.116      459781.083     1905129.298      459613.476
      1904740.21      459224.388
#Sta/Elev= 30
       0  898.23    87.5  855.14   116.7  841.45   175.1  815.09   194.8  805.72
   204.8  803.17   212.4  802.91   214.8  802.83   224.8  804.28   227.4  804.91
   244.8  809.24   254.8  811.07   264.8  811.82   284.8  812.23   314.8  812.04
   394.9  809.23   484.9  807.68   504.9  807.57   514.9  807.75     525  808.34
     535  810.59     545  815.78     555  823.13     565  831.03     575  837.42
     605  852.02     665  882.06     685  890.78     695  894.86     735  909.93
#Mann= 3 , 0 , 0
       0      .1       0   212.4    .045       0   227.4      .1       0
#XS Ineff= 2 , 0
                          294.79          812.28
Permanent Ineff=
       F       F
Bank Sta=212.4,227.4
XS Rating Curve= 0 ,0
Exp/Cntr=0.3,0.1

Type RM Length L Ch R = 1 ,18462.9 ,307.2,300.6,294
XS GIS Cut Line= 4
      1905478.48      459497.747      1905414.63      459413.944
     1904949.719      459282.252     1904831.995      459208.425
#Sta/Elev= 30
       0  881.44    57.5  851.59    95.8  830.85   105.4  826.37   115.2  823.18
   125.1   821.1   213.8  806.82   233.6  803.27   253.3  799.12   259.8  798.22
   263.1  797.76     273  797.64   274.8  797.77   282.9  798.38   312.4  801.49
   361.8  805.64   381.5  806.99   411.1  808.55   450.5  807.82     490   807.4
   568.8  807.48   578.7  807.97   588.6  809.67   618.3  818.91   628.3  822.87
   638.2  827.44     658  837.07   707.7  862.21   717.6  866.78   727.5  871.69
#Mann= 3 , 0 , 0
       0      .1       0   259.8    .045       0   274.8      .1       0
Bank Sta=259.8,274.8
XS Rating Curve= 0 ,0
Exp/Cntr=0.3,0.1

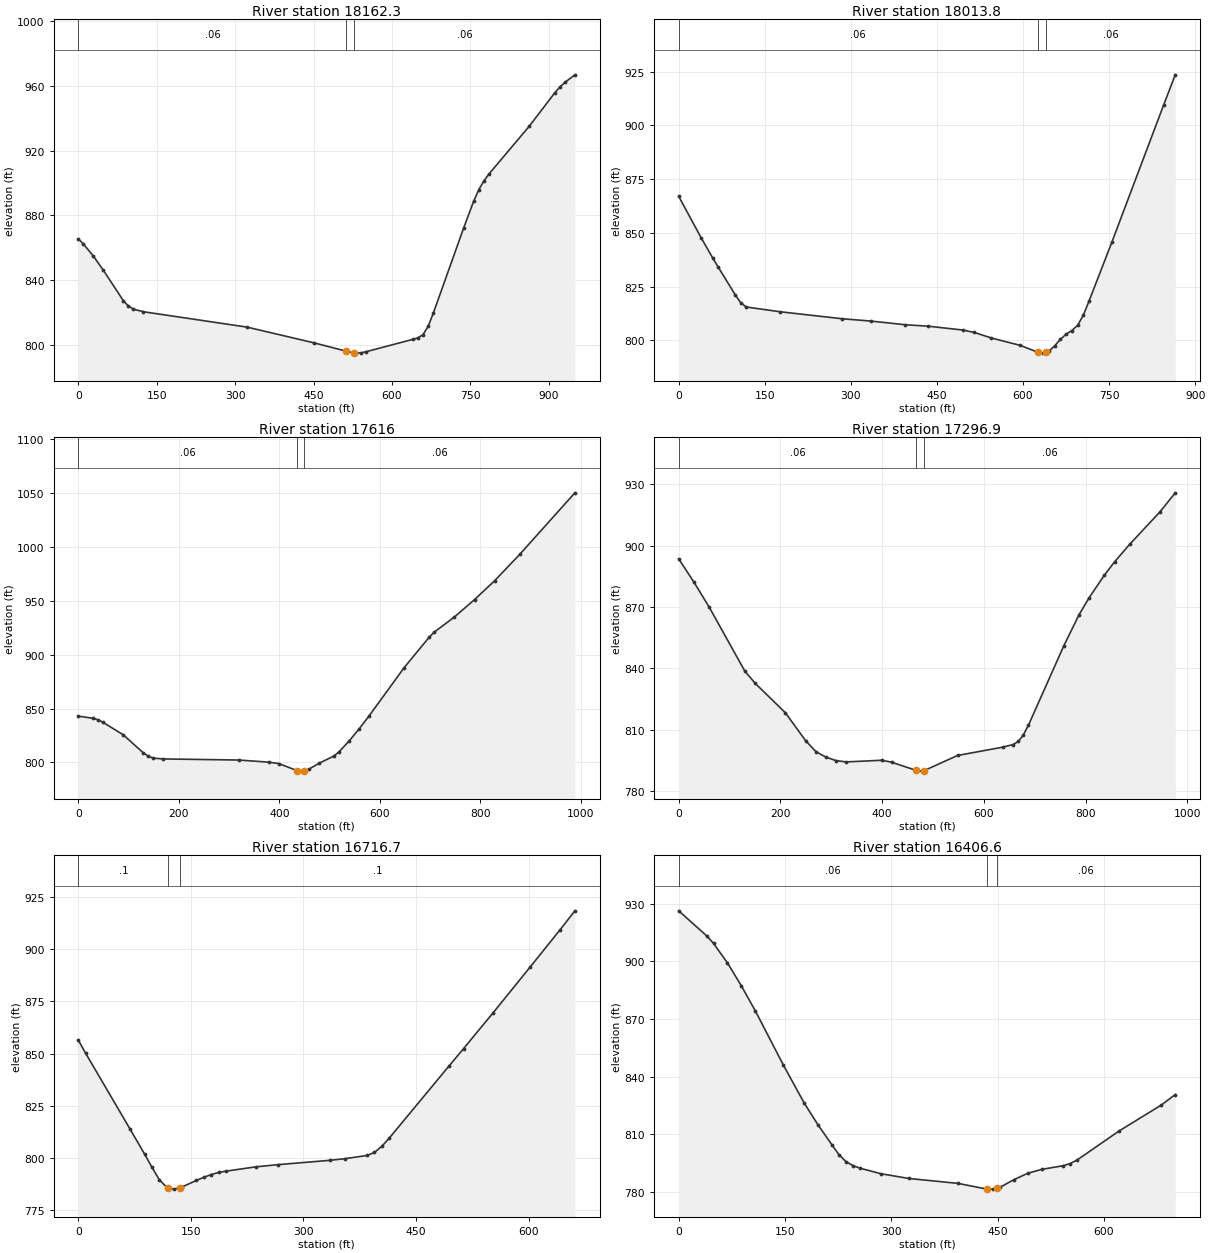
Type RM Length L Ch R = 1 ,18162.3 ,147.9,148.4,149
XS GIS Cut Line= 4
     1905731.887      459124.621     1905622.201      459065.607
     1905067.443      459076.734     1904808.051      458998.916
#Sta/Elev= 30
       0  865.42     9.6  862.29    28.7  854.81    47.9  846.02    86.2   827.2
    95.8   823.9   105.4  822.04   124.6  820.43   322.7  810.95   451.5  801.19
     513  796.05     528     795   530.8  794.88   540.7  795.04   550.6  795.76
   639.8  803.35   649.7  804.28   659.6  806.33   669.5  811.45   679.4  819.69
   737.4  872.22   756.8  888.95   766.5   895.9   776.1  901.22   785.8  905.51
   863.2  935.14   911.6   955.6   921.2  959.14   930.9  962.04   950.2  966.75
#Mann= 3 , 0 , 0
       0     .06       0     513    .045       0     528     .06       0
Bank Sta=513,528
XS Rating Curve= 0 ,0
Exp/Cntr=0.3,0.1

Type RM Length L Ch R = 1 ,18013.8 ,398.3,397.8,397.3
XS GIS Cut Line= 3
     1905783.765      459034.832     1905516.392      458937.061
     1904935.752      458939.056
#Sta/Elev= 30
       0     867    39.3  847.63    58.9   838.5    68.7  834.15    98.2  821.33
     108   817.5   117.8  815.53   176.7  813.32   284.7  810.07   334.7  808.99
   394.8  807.28   434.9   806.6   494.9  804.82   514.9   803.7     545   801.1
     595  797.69   625.6   794.5   635.1  794.07   640.6  794.54   645.1  794.92
   655.1  797.44   665.1  800.49   675.1  802.86   685.1  804.59   695.1  806.98
   705.2  811.75   715.2  818.39   755.2  845.95   845.3  909.69   865.3  923.56
#Mann= 3 , 0 , 0
       0     .06       0   625.6    .045       0   640.6     .06       0
Bank Sta=625.6,640.6
XS Rating Curve= 0 ,0
Exp/Cntr=0.3,0.1

Type RM Length L Ch R = 1 ,17616   ,318.5,319.2,319.8
XS GIS Cut Line= 3
     1905548.317      458474.145     1905438.574      458541.986
     1904579.379      458553.693
#Sta/Elev= 30
       0  842.99    29.8  841.02    39.7  839.52    49.6  837.12    89.3  825.71
     129  809.08     139  805.92     149  804.05     169   803.3   318.9  802.29
   378.8  800.32   398.8  799.03   434.8  792.55   438.8  791.99   449.8  792.26
   458.7  793.77   478.7  799.14   508.7  806.04   518.7  809.78   538.7  819.84
   558.7  831.08   578.6  843.19   648.6  888.08   698.5  916.39   708.5  920.99
   748.5  935.02   788.5  951.14   828.4  968.58   878.4  993.05   988.3 1050.22
#Mann= 3 , 0 , 0
       0     .06       0   434.8    .045       0   449.8     .06       0
Bank Sta=434.8,449.8
XS Rating Curve= 0 ,0
Exp/Cntr=0.3,0.1

Type RM Length L Ch R = 1 ,17296.9 ,591.8,580.1,565.8
XS GIS Cut Line= 3
     1905624.139      458222.734     1905364.747      458234.706
     1904648.425      458220.739
#Sta/Elev= 30
       0   893.5      30  882.07    59.9   869.9   129.8  838.68   149.8   832.8
   209.7  818.26   249.7  804.56   269.6  799.29   289.5  796.56   309.4  794.89
   329.3  794.25     399  795.06   418.9  794.08   466.7  790.12   478.6  789.75
   481.7  789.93   548.2   797.4   637.8   801.5   657.7  802.76   667.6  804.26
   677.6  807.48   687.6  812.26   757.2   851.1   787.1  866.23     807  874.57
   836.8  885.52   856.7  891.99   886.6  900.61   946.3  916.52   976.1  925.75
#Mann= 3 , 0 , 0
       0     .06       0   466.7    .045       0   481.7     .06       0
Bank Sta=466.7,481.7
XS Rating Curve= 0 ,0
Exp/Cntr=0.3,0.1

Type RM Length L Ch R = 1 ,16716.7 ,300.6,310,322.1
XS GIS Cut Line= 3
     1905123.312      457646.085     1905011.861      457708.143
     1904575.422      458016.325
#Sta/Elev= 30
       0  856.38     9.8  850.08    68.7  813.87    88.3  801.72    98.1  795.39
   107.9  789.44   117.8  785.78   120.1  785.58   127.6  784.92   135.1  785.63
   137.5  785.86   157.2  789.07   167.1  790.57     177  791.91   186.9  792.91
   196.8  793.55   236.4  795.61   266.1  796.67   335.3  798.75   355.1  799.52
   384.8  801.08   394.7  802.55   404.6  805.53   414.5  809.46   493.6  843.85
   513.4  852.37     553  869.66   602.5  891.69   642.1  909.44   661.8  918.51
#Mann= 3 , 0 , 0
       0      .1       0   120.1    .045       0   135.1      .1       0
Bank Sta=120.1,135.1
XS Rating Curve= 0 ,0
Exp/Cntr=0.3,0.1

Type RM Length L Ch R = 1 ,16406.6 ,245.9,259.5,273.1
XS GIS Cut Line= 3
     1905239.041      457544.324     1905033.523      457450.543
     1904560.631       457490.45
#Sta/Elev= 30
       0  926.28    39.3  913.32    49.1  909.36    68.8  899.18    88.4  887.26
     108  874.32   147.3  846.34   176.8  826.49   196.4  815.06   216.1  804.64
   225.9  799.59   235.8  795.93   245.7  793.84   255.6   792.5   285.2   789.6
   324.8  787.12     394  784.57   434.3  781.65   443.4  781.59   449.3  782.16
   453.3  782.55   473.1  786.56   492.8  789.89   512.6  791.89   542.3  793.76
   552.2  794.89   562.1  796.73   621.4  811.86   680.7  825.27   700.5  830.76
#Mann= 3 , 0 , 0
       0     .06       0   434.3    .045       0   449.3     .06       0
Bank Sta=434.3,449.3
XS Rating Curve= 0 ,0
Exp/Cntr=0.3,0.1

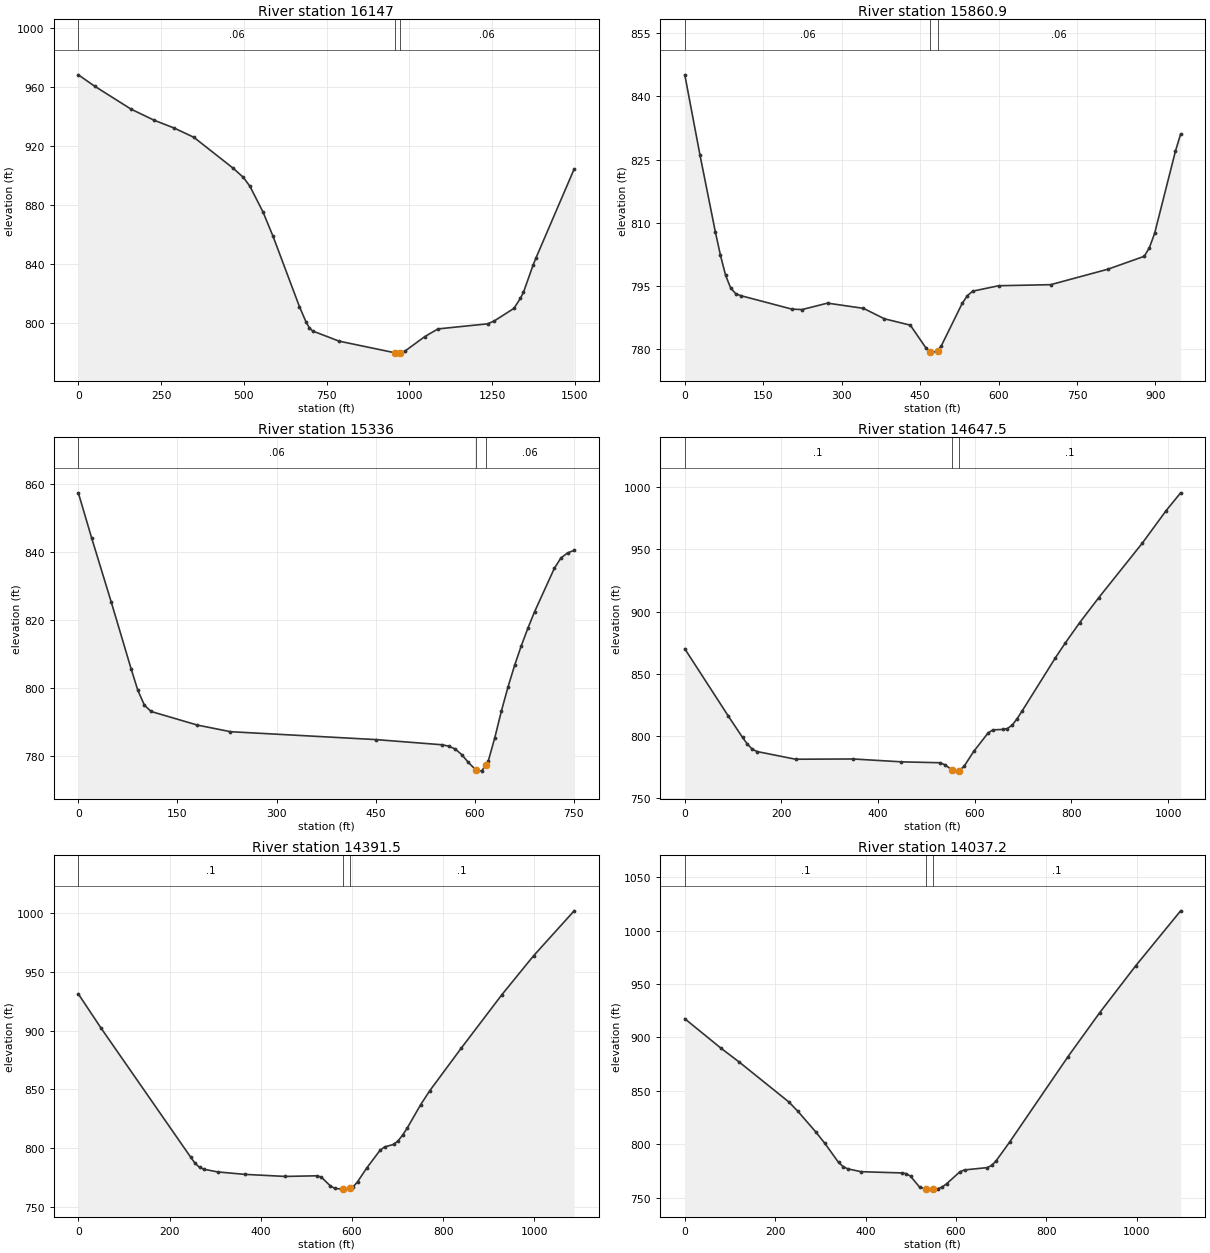
Type RM Length L Ch R = 1 ,16147   ,284,286.1,288.2
XS GIS Cut Line= 3
     1905671.766      457709.013     1904532.696      457049.483
     1904355.112      457089.389
#Sta/Elev= 30
       0  968.49    49.9   960.7   159.5   945.2   229.3  937.67   289.2  932.44
     349  926.13   468.7     905   498.6  898.92   518.5  892.91   558.4  875.29
   588.3  859.01   668.1   811.3     688  800.92     698  796.98     708  794.76
   787.7  787.89   955.5  780.04   967.2  779.75   970.5  779.86   987.2  781.16
    1047     791  1086.9  796.18  1236.5  799.61  1256.4  801.52  1316.2   810.1
  1335.4   816.8    1345  820.99  1373.7  839.18  1383.3  844.56  1498.2  904.62
#Mann= 3 , 0 , 0
       0     .06       0   955.5    .045       0   970.5     .06       0
Bank Sta=955.5,970.5
XS Rating Curve= 0 ,0
Exp/Cntr=0.3,0.1

Type RM Length L Ch R = 1 ,15860.9 ,500.7,524.7,548.7
XS GIS Cut Line= 3
     1905187.163      457384.697     1905123.312      457079.413
     1904605.233      456710.075
#Sta/Elev= 30
       0  845.11    29.2  825.96    58.5  807.77    68.2  802.26      78  797.54
    87.7   794.5    97.5  793.14   107.2  792.68   204.7  789.49   224.2  789.38
   272.9  790.91   341.7  789.67   381.5   787.2   431.2  785.68     461  780.29
   468.6  779.34     471  779.04   483.6  779.66   490.8  780.85   530.6  790.89
   540.5   792.7   550.5  793.75   600.2  795.04   699.6  795.29     809  798.96
   878.6  802.03   888.5  804.11   898.4  807.48   938.2     827   948.1  831.04
#Mann= 3 , 0 , 0
       0     .06       0   468.6    .045       0   483.6     .06       0
Bank Sta=468.6,483.6
XS Rating Curve= 0 ,0
Exp/Cntr=0.3,0.1

Type RM Length L Ch R = 1 ,15336   ,686,688.5,691
XS GIS Cut Line= 2
      1905354.77      457418.618     1905434.583      456672.366
#Sta/Elev= 30
       0  857.44      20  844.28      50  825.22      80  805.65    90.1  799.38
   100.1  795.01   110.1  793.18   180.1  789.19   230.2  787.24   450.3  784.92
   550.4   783.4   560.4     783   570.4  782.16   580.4  780.49   590.4   778.2
   601.4  776.08   610.4  775.65   616.4  777.39   620.4  778.55   630.4  785.48
   640.4  793.34   650.4   800.4   660.4  806.74   670.4  812.46   680.5  817.67
   690.5  822.46   720.5  835.25   730.5  838.31   740.5  839.77   750.5  840.53
#Mann= 3 , 0 , 0
       0     .06       0   601.4    .045       0   616.4     .06       0
Bank Sta=601.4,616.4
XS Rating Curve= 0 ,0
Exp/Cntr=0.3,0.1

Type RM Length L Ch R = 1 ,14647.5 ,257.4,256,254.6
XS GIS Cut Line= 2
     1905947.382        457582.9     1906168.863      456581.246
#Sta/Elev= 30
       0  870.16    89.6  816.42   119.5  798.95   129.5  793.63   139.4  789.62
   149.4  787.67   229.1  781.49   348.6  781.69   448.2  779.39   527.9  778.67
   537.8  777.11   551.9  773.21   557.7  771.93   566.9  772.14   577.7  775.73
   597.6   787.7   627.5  802.58   637.4  805.06   657.3  805.42   667.3  806.14
   677.3  808.86   687.2  813.88   697.2  819.82   766.9  863.07   786.8  874.62
   816.7  891.06   856.5  911.28   946.2  954.87     996  981.23  1025.8  995.43
#Mann= 3 , 0 , 0
       0      .1       0   551.9    .045       0   566.9      .1       0
Bank Sta=551.9,566.9
XS Rating Curve= 0 ,0
Exp/Cntr=0.3,0.1

Type RM Length L Ch R = 1 ,14391.5 ,362,354.3,346.5
XS GIS Cut Line= 3
     1906264.639      457697.964     1906266.634      457392.679
     1906388.043      456620.154
#Sta/Elev= 30
       0   931.2    49.2  902.51   246.2   792.5     256  787.19   265.9  783.69
   275.8   782.1   305.3  779.87   364.7  777.78   453.8  776.02   523.1  776.56
     533  775.38   552.8  767.89   562.7  765.82     581  765.22     596  766.07
   602.3  767.04   612.2  771.41     632  782.95   661.6  798.24   671.6  801.11
   691.4  803.26   701.2  806.28   711.1  811.14     721  816.99   750.7  837.05
   770.5  848.82   839.8  885.16   928.9  930.61   998.2   963.6  1087.3 1001.87
#Mann= 3 , 0 , 0
       0      .1       0     581    .045       0     596      .1       0
Bank Sta=581,596
XS Rating Curve= 0 ,0
Exp/Cntr=0.3,0.1

Type RM Length L Ch R = 1 ,14037.2 ,328.8,320.5,311.8
XS GIS Cut Line= 3
     1906805.372      457668.034     1906697.624      457334.814
      1906557.95      456600.834
#Sta/Elev= 30
       0  917.56      80  889.97   120.1  877.08   230.1  839.63   250.2  830.86
   290.2  811.32   310.2  800.66   340.2  782.96   350.2  779.04   360.2  776.95
     390  774.22   479.7  773.05   489.7  772.41   499.6  769.99   519.6  759.79
   533.7     758   548.7  757.87   559.4  758.19   569.4  759.75   579.3  762.86
   609.2  774.22   619.2  775.87     669  778.02     679  780.02   688.9  784.32
   718.8  801.89   848.3  882.14     918  923.08   997.7  967.04  1097.4 1018.68
#Mann= 3 , 0 , 0
       0      .1       0   533.7    .045       0   548.7      .1       0
Bank Sta=533.7,548.7
XS Rating Curve= 0 ,0
Exp/Cntr=0.3,0.1

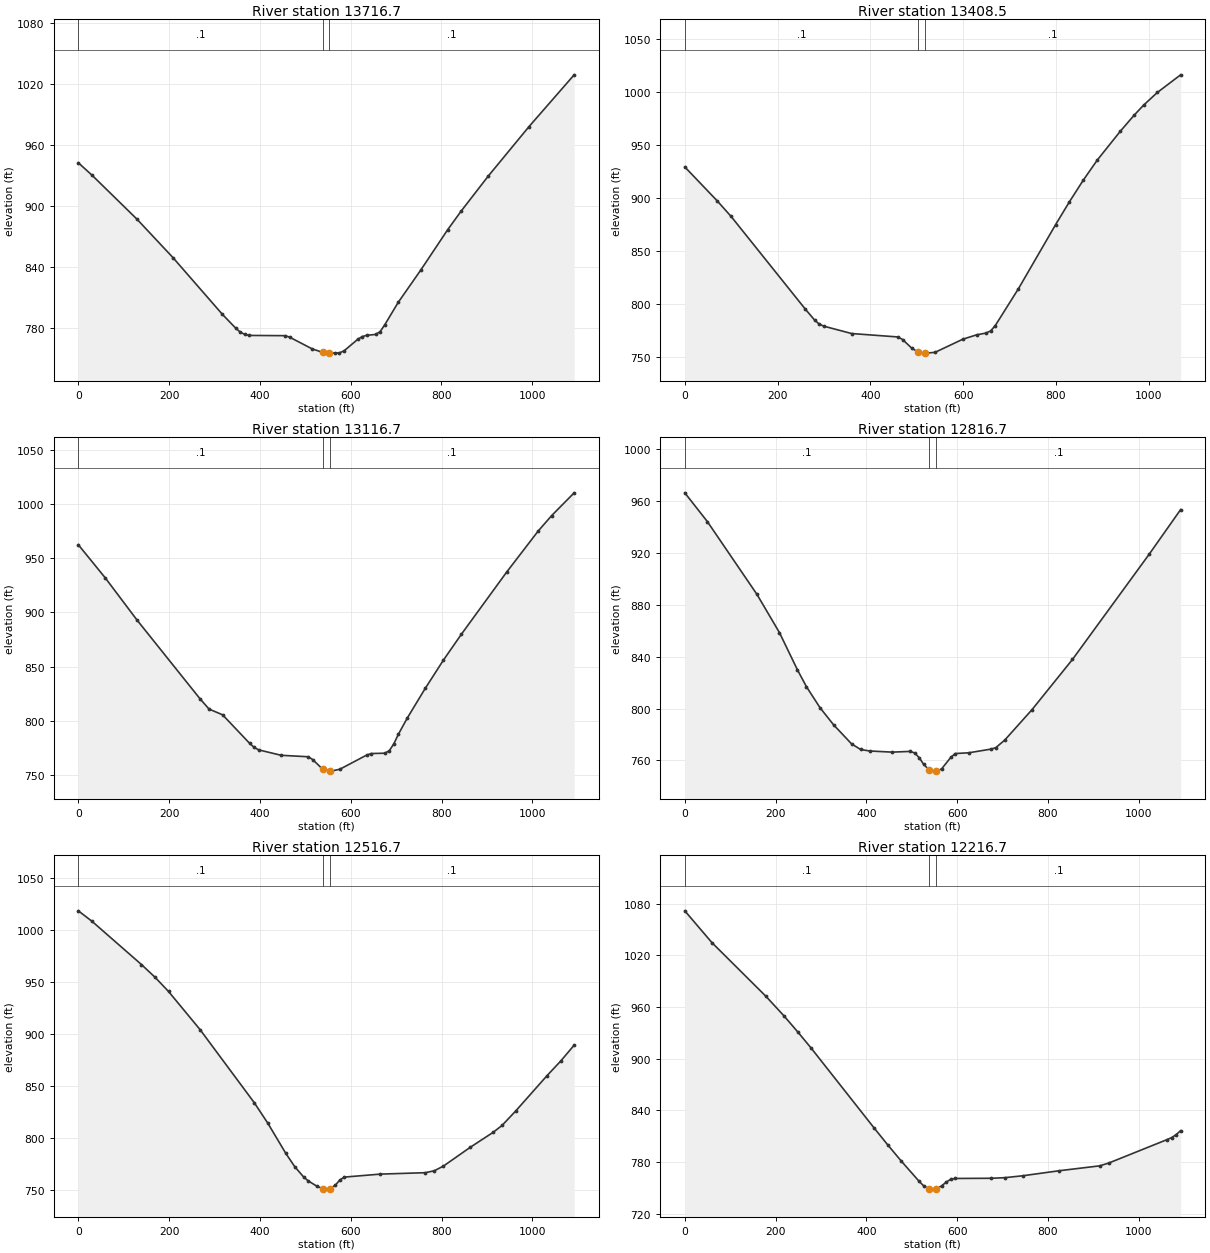
Type RM Length L Ch R = 1 ,13716.7 ,311.6,308.1,305.1
XS GIS Cut Line= 3
     1907236.257      457474.008      1906948.04      457010.817
     1906650.293      456552.069
#Sta/Elev= 30
       0   942.6    29.8  930.57     129  887.24   208.3  849.43   317.4  793.53
   347.2  779.73   357.1  775.97     367  773.75   376.9  772.79   456.3  772.54
   466.2  770.94   515.8   759.4     538  756.25     553   755.7   565.4  755.38
   575.4  755.69   585.3  757.58   615.2  768.81   625.1  771.56     635  772.88
   654.9  773.76   664.9  776.52   674.8  783.02   704.6   805.2   754.4  837.07
     814  876.94   843.8  895.32   903.5  929.75     993  978.24  1092.4 1029.14
#Mann= 3 , 0 , 0
       0      .1       0     538    .045       0     553      .1       0
Bank Sta=538,553
XS Rating Curve= 0 ,0
Exp/Cntr=0.3,0.1

Type RM Length L Ch R = 1 ,13408.5 ,300.3,291.9,283.7
XS GIS Cut Line= 2
     1907537.656      457231.057      1906843.06      456418.717
#Sta/Elev= 30
       0  929.41    69.9  897.42    99.9  882.72   259.7  795.47   279.7  785.18
   289.7  781.33   299.7  779.36   359.6  772.43   459.5   769.2   469.5  766.79
   489.5  758.52   502.8     755   517.8     754   519.4  753.97   539.4   754.7
   599.3  767.09   629.3  771.23   649.3  772.88   659.3   774.9   669.3  779.96
   719.2  814.66   799.1  874.89   829.1  896.58     859  916.97     889   935.8
     939  963.16   968.9   978.3   988.9  987.59  1018.9  999.67  1068.8  1016.2
#Mann= 3 , 0 , 0
       0      .1       0   502.8    .045       0   517.8      .1       0
Bank Sta=502.8,517.8
XS Rating Curve= 0 ,0
Exp/Cntr=0.3,0.1

Type RM Length L Ch R = 1 ,13116.7 ,298.2,300,301.4
XS GIS Cut Line= 3
     1907859.335      456866.838     1907376.796      456611.377
     1906897.647      456349.467
#Sta/Elev= 30
       0  962.58    59.6   931.8     129  893.11     268  820.19   287.9  810.68
   317.7  805.39   377.2  779.04   387.2  775.28   397.1  772.99   446.7  767.95
   506.3   766.6   516.2     764   538.5  754.93   553.5   753.4   555.9  753.32
   575.8  755.03   635.3  768.22   645.3  769.58   675.1  769.89     685  772.26
   694.9   778.6   704.8  787.34   724.7  802.56   764.4  830.07   804.1  855.96
   843.8  879.96   943.1  937.17  1012.6  975.18  1042.4  989.52    1092 1010.58
#Mann= 3 , 0 , 0
       0      .1       0   538.5    .045       0   553.5      .1       0
Bank Sta=538.5,553.5
XS Rating Curve= 0 ,0
Exp/Cntr=0.3,0.1

Type RM Length L Ch R = 1 ,12816.7 ,298.2,300,301.8
XS GIS Cut Line= 3
     1907989.504      456644.707     1907528.233      456352.568
     1907066.962       456060.43
#Sta/Elev= 30
       0  966.45    49.6  944.31   158.8  888.18   208.5   858.6   248.2  829.82
     268  816.85   297.8  800.69   327.6  787.53   367.3  772.79   387.2  768.46
     407   767.3   456.6  766.42   496.4  766.98   506.3  765.77   516.2  762.17
   526.2  756.92   538.5  752.65   553.5  751.78   555.9  751.76   565.8  753.58
   585.7  762.32   595.6  765.32   625.4  765.91     675  768.78     685  769.88
   704.8  775.77   764.4  799.06   853.8  837.92  1022.5  918.97    1092  953.52
#Mann= 3 , 0 , 0
       0      .1       0   538.5    .045       0   553.5      .1       0
Bank Sta=538.5,553.5
XS Rating Curve= 0 ,0
Exp/Cntr=0.3,0.1

Type RM Length L Ch R = 1 ,12516.7 ,298.4,300,301.3
XS GIS Cut Line= 3
     1908139.291      456438.011     1907703.411      456109.188
      1907267.53      455780.366
#Sta/Elev= 30
       0 1018.56    29.8 1008.59     139   966.9   168.8  954.71   198.6  941.02
     268  904.35   387.2  834.15     417  814.49   456.6  785.48   476.5   772.5
   496.4   762.4   506.3  758.81   526.2   753.4   538.5  751.35     546  750.83
   553.5  751.25   565.8  754.49   575.8  759.56   585.7   762.4   665.1  765.28
   764.4  766.64   784.2  768.54   804.1  773.01   863.7  791.23   913.3  805.38
   933.2  812.12     963  825.88  1032.4  860.08  1062.2  873.96    1092  889.34
#Mann= 3 , 0 , 0
       0      .1       0   538.5    .045       0   553.5      .1       0
Bank Sta=538.5,553.5
XS Rating Curve= 0 ,0
Exp/Cntr=0.3,0.1

Type RM Length L Ch R = 1 ,12216.7 ,488,495.5,503.3
XS GIS Cut Line= 3
     1908299.813      456231.561     1907887.924       455872.76
     1907471.248      455520.046
#Sta/Elev= 30
       0 1071.62    59.6 1034.82   178.8  972.42   218.5  949.74   248.3  931.48
   278.1  912.54   417.1  819.67   446.9  800.22   476.7  781.42   516.5  757.63
   526.4  752.51   536.3  749.51   538.8  749.33   546.2  748.78   553.8  749.41
   556.2  749.61   566.1  752.73     576  756.99     586  760.28   595.9  761.15
   675.3  761.37   705.1  762.07   744.8   764.3   824.2  770.08   913.5  775.76
   933.4  778.93  1062.4  806.24  1072.3  808.54  1082.2  811.93  1092.2  816.56
#Mann= 3 , 0 , 0
       0      .1       0   538.8    .045       0   553.8      .1       0
Bank Sta=538.8,553.8
XS Rating Curve= 0 ,0
Exp/Cntr=0.3,0.1

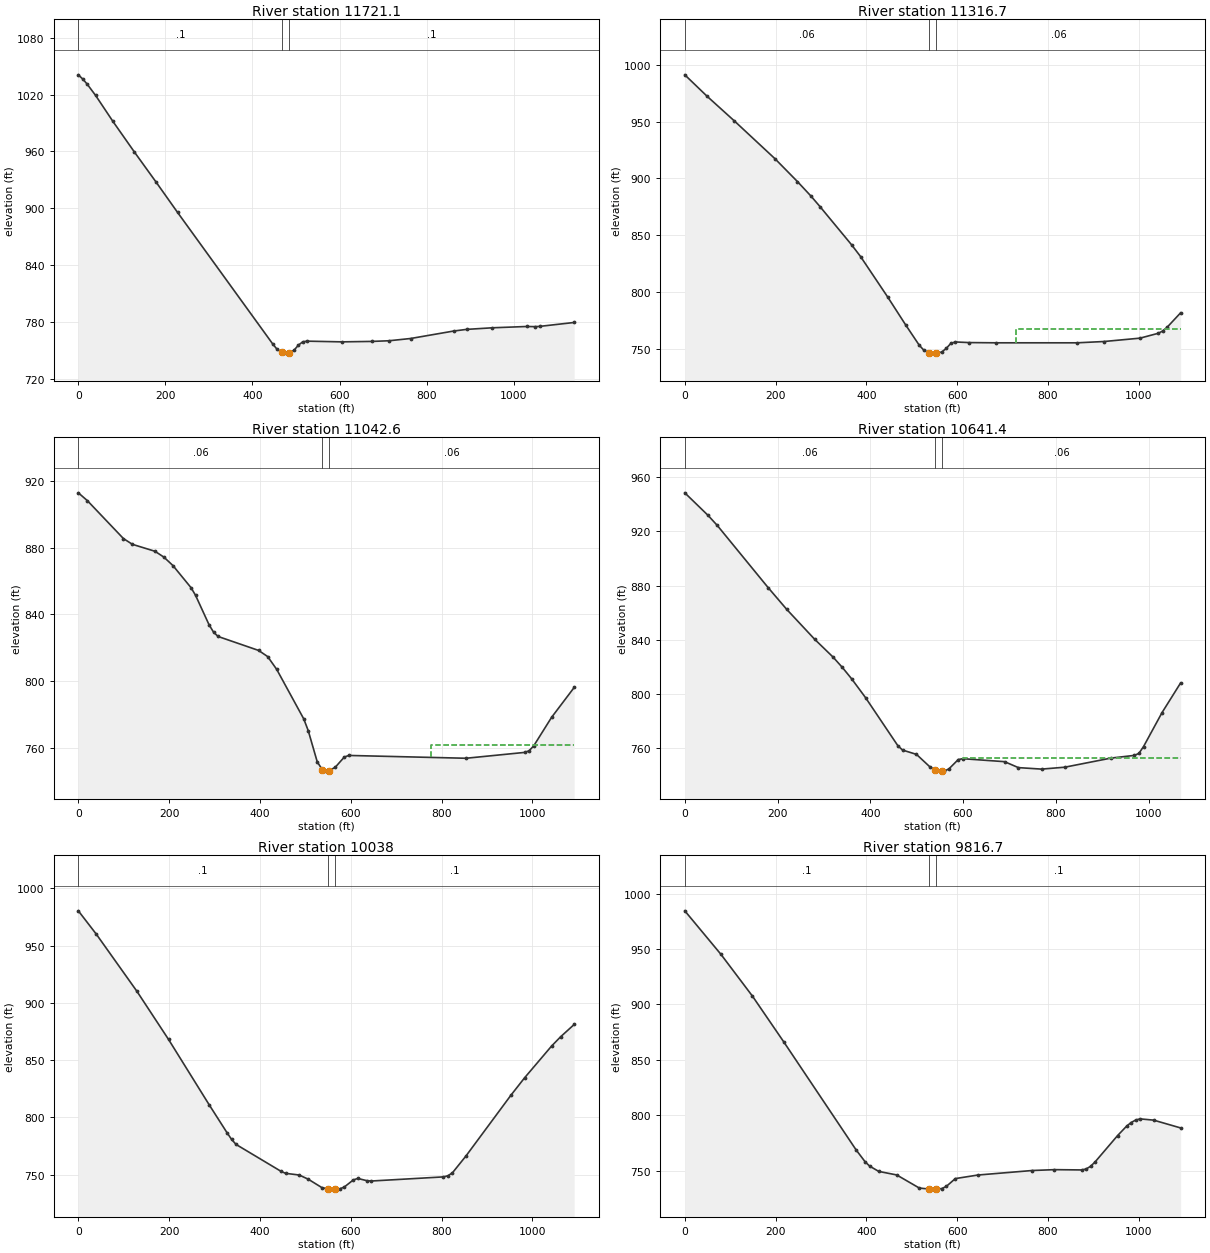
Type RM Length L Ch R = 1 ,11721.1 ,400.1,404.5,408.8
XS GIS Cut Line= 3
     1908506.054      455972.007     1908149.593      455353.559
     1907817.002      455088.743
#Sta/Elev= 30
       0 1040.84     9.9 1036.51    19.8 1031.32    39.7 1019.07    79.3  991.78
   128.9  959.28   178.5  927.68     228  895.56   446.1  757.01     456  751.39
     466   748.2   468.5  747.91   475.9  747.04   483.5  747.23   485.8  747.29
   495.7  750.21   505.6   755.5   515.5  758.97   525.4  759.68   604.8  758.94
   674.2   759.4   713.8   760.1   763.3  762.48   862.1  770.36   891.8   772.1
   951.1  773.79  1030.2  775.16    1050     775  1059.9  775.28    1139   779.4
#Mann= 3 , 0 , 0
       0      .1       0   468.5    .045       0   483.5      .1       0
Bank Sta=468.5,483.5
XS Rating Curve= 0 ,0
Exp/Cntr=0.3,0.1

Type RM Length L Ch R = 1 ,11316.7 ,276.3,274.1,271.8
XS GIS Cut Line= 3
     1908819.748      455930.111     1908643.568      455413.316
     1908467.538      454896.471
#Sta/Elev= 30
       0  991.24    49.6  972.17   109.2  950.62   198.6  917.35   248.2  897.18
     278  884.39   297.8  875.16   367.3  841.55   387.2  831.14   446.7  795.64
   486.4  771.01   516.2  753.18   526.2  748.81   536.1  746.75   538.5  746.61
   553.5  746.14   555.9  746.13   565.8  747.07   575.8  750.26   585.7  754.63
   595.6  755.98   625.4  755.43     685  755.22   863.7  755.21   923.2  756.36
  1002.6  759.32  1042.4  763.56  1052.3  765.57  1062.2  768.88    1092  781.64
#Mann= 3 , 0 , 0
       0     .06       0   538.5    .045       0   553.5     .06       0
#XS Ineff= 2 , 0
                             730          767.55
Permanent Ineff=
       F       F
Bank Sta=538.5,553.5
XS Rating Curve= 0 ,0
Exp/Cntr=0.3,0.1

Type RM Length L Ch R = 1 ,11042.6 ,403.8,401.2,398.6
XS GIS Cut Line= 3
      1909128.41      455821.548     1908902.474      455324.487
     1908675.738      454827.791
#Sta/Elev= 30
       0  912.76    19.8   908.1    99.3  885.36   119.1   881.9   168.8  877.74
   188.6   874.2   208.5  869.14   248.2  855.93   258.1  851.38   287.9  833.71
   297.8  829.28   307.8  826.69   397.1  818.32     417  814.64   436.8  807.02
   496.4  777.33   506.3  770.29   526.2  751.54   537.7  746.74     546  746.01
   552.7  746.38   565.8  748.31   585.7  754.41   595.6  755.41   853.8  753.72
   982.8  757.22   992.7   758.2  1002.7  761.05  1042.4  778.28    1092  796.12
#Mann= 3 , 0 , 0
       0     .06       0   537.7    .045       0   552.7     .06       0
#XS Ineff= 2 , 0
                          776.08           761.4
Permanent Ineff=
       F       F
Bank Sta=537.7,552.7
XS Rating Curve= 0 ,0
Exp/Cntr=0.3,0.1

Type RM Length L Ch R = 1 ,10641.4 ,598.9,603.3,607.7
XS GIS Cut Line= 2
     1909526.996      455584.914     1908974.866      454669.329
#Sta/Elev= 30
       0  948.51      50  931.91      70  924.44   179.9  878.43   219.8  862.45
   279.8  840.45   319.8  827.17   339.7  819.58   359.7   811.2   389.7  797.29
   459.6  761.68   469.6  758.54   499.6  755.36   529.6   745.8   539.8  744.07
   554.8   743.2   559.6  742.99   569.6  744.67   589.6  751.52   599.5  752.17
   689.5  749.98   719.4  745.58   769.4  744.48   819.4  745.89   919.3  752.63
   969.3   754.6   979.2  756.08   989.2  761.11  1029.2  786.27  1069.2  808.13
#Mann= 3 , 0 , 0
       0     .06       0   539.8    .045       0   554.8     .06       0
#XS Ineff= 2 , 0
                          599.61          752.32
Permanent Ineff=
       F       F
Bank Sta=539.8,554.8
XS Rating Curve= 0 ,0
Exp/Cntr=0.3,0.1

Type RM Length L Ch R = 1 ,10038   ,214.3,221.4,229.2
XS GIS Cut Line= 3
      1909961.25      455357.029     1909775.652      454843.541
     1909590.055      454330.053
#Sta/Elev= 30
       0  980.45    39.7  960.01     129  910.19   198.6  868.18   287.9  811.22
   327.6  786.58   337.5  780.85   347.4  776.42   446.7  752.87   456.6  751.18
   486.4  749.71   506.3  746.08   536.1  738.78   549.9  737.52   564.9  737.39
   575.8  737.63   585.7  739.22   605.6  745.42   615.5  746.73   635.4  744.77
   645.3  744.47   804.1  748.08     814  749.05     824  751.68   853.8  766.38
     953  819.55   982.8   834.6  1042.4   862.4  1062.2  870.46    1092  881.18
#Mann= 3 , 0 , 0
       0      .1       0   549.9    .045       0   564.9      .1       0
Bank Sta=549.9,564.9
XS Rating Curve= 0 ,0
Exp/Cntr=0.3,0.1

Type RM Length L Ch R = 1 ,9816.7  ,300.2,300,299.9
XS GIS Cut Line= 3
      1910007.65      455342.004     1909988.927      454795.936
     1909988.927      454250.004
#Sta/Elev= 30
       0  984.38    79.5  945.21     149   907.5   218.6  865.87   377.5  768.78
   397.4  758.05   407.3  754.21   427.2  749.45   466.9  746.25   516.6  734.45
   538.9   733.5   546.4  733.47   553.9  733.48   566.2  733.98   576.2  735.95
     596  742.97   645.6  746.18   764.8  750.24   814.4  751.03     874  750.77
   883.9  751.57   893.8  754.01   903.7  757.92   953.4  781.74   973.2   790.2
   983.1  793.49   993.1  795.71    1003   796.8  1032.8  795.68  1092.3  788.64
#Mann= 3 , 0 , 0
       0      .1       0   538.9    .045       0   553.9      .1       0
Bank Sta=538.9,553.9
XS Rating Curve= 0 ,0
Exp/Cntr=0.3,0.1