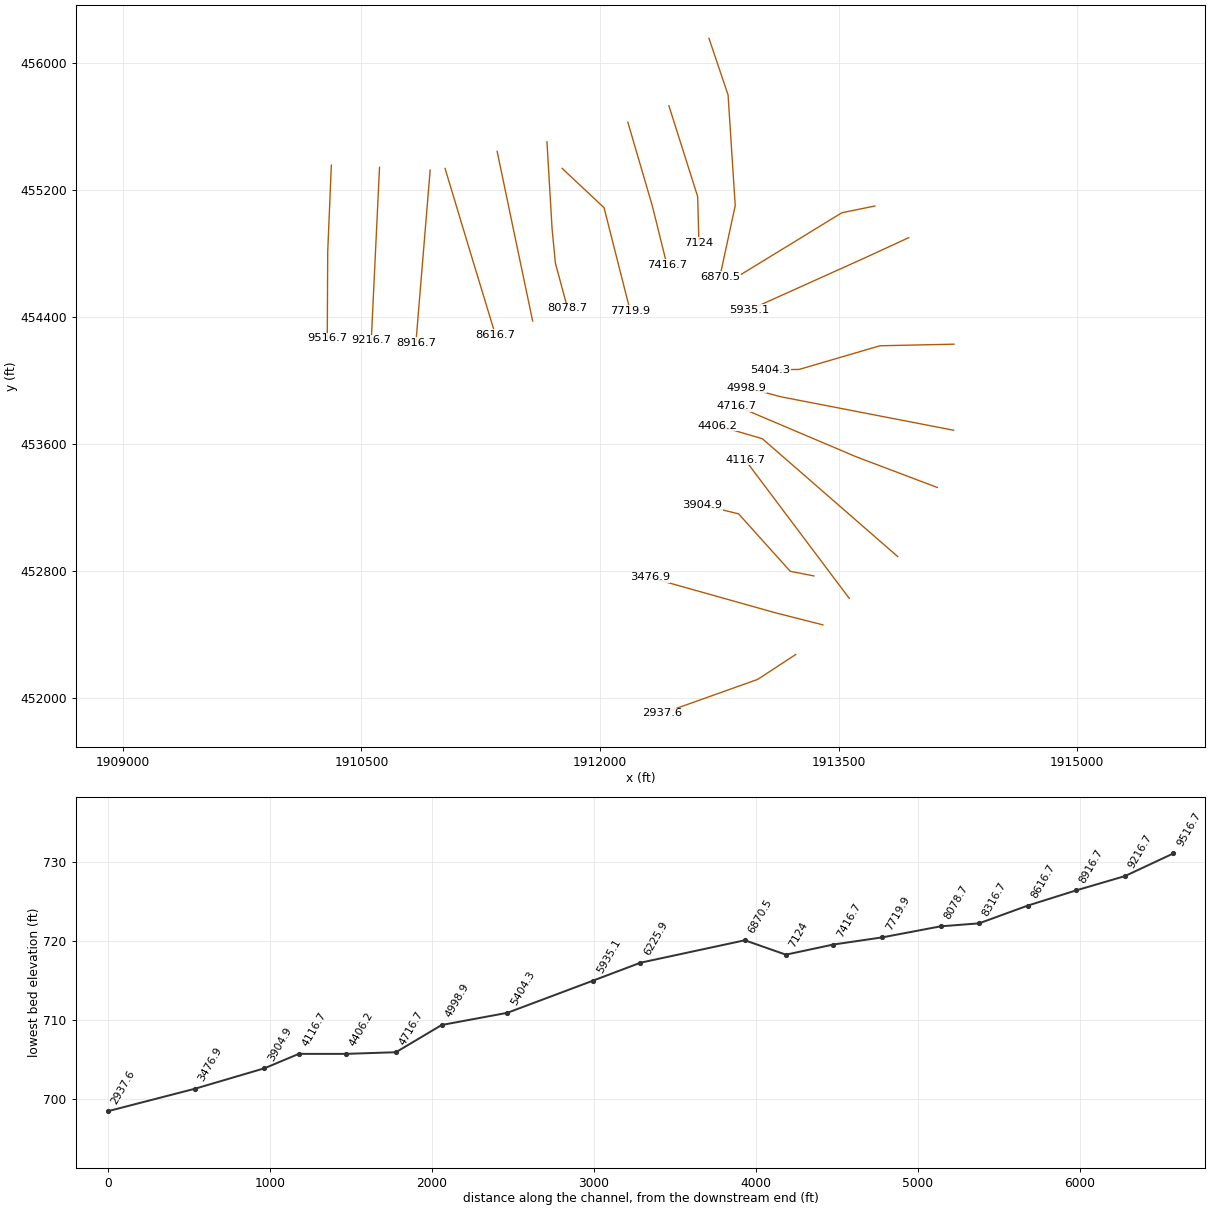
HEC-RAS study BellsCreek.prj: BellsCreek

--- BellsCreek.g01 (geometry) --- (continued)

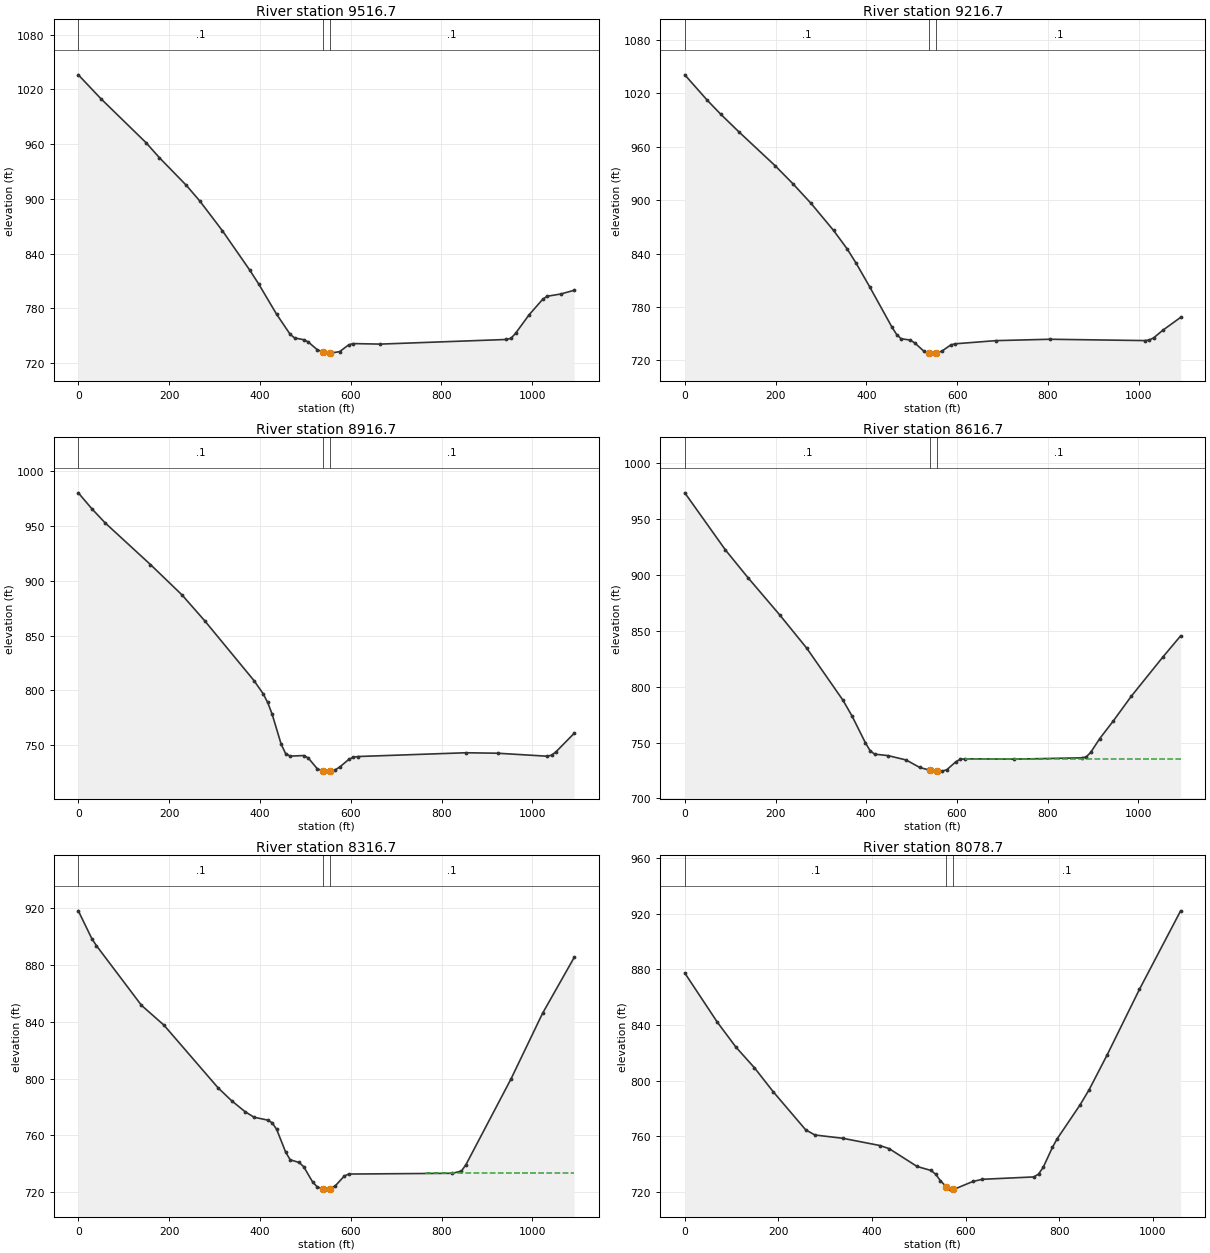
Type RM Length L Ch R = 1 ,9516.7  ,300.1,300,299
XS GIS Cut Line= 3
     1910310.824      455355.839     1910288.096       454810.39
     1910285.236      454263.957
#Sta/Elev= 30
       0 1035.94    49.6 1009.86   148.9  961.75   178.7  945.12   238.2  914.76
     268  897.49   317.6  865.04   377.2  822.35     397  807.11   436.7  773.77
   466.5  751.82   476.4   747.7   496.3  745.81   506.2  743.42   526.1  734.95
   538.4  732.39   553.4  731.21   555.9  731.07   575.7  732.73   595.6  740.12
   605.5  741.52   665.2  740.96   943.3  746.03   953.3  747.33   963.2  752.72
     993  772.98  1022.8  789.91  1032.8  793.37  1062.6  795.81  1092.4  799.92
#Mann= 3 , 0 , 0
       0      .1       0   538.4    .045       0   553.4      .1       0
Bank Sta=538.4,553.4
XS Rating Curve= 0 ,0
Exp/Cntr=0.3,0.1

Type RM Length L Ch R = 1 ,9216.7  ,300.8,300,299.2
XS GIS Cut Line= 3
     1910613.764      455342.325     1910587.794      454796.943
     1910561.823      454251.561
#Sta/Elev= 30
       0 1040.54    49.6 1011.94    79.4   996.2   119.1  976.58   198.6  938.71
   238.2  918.27     278   896.3   327.6  865.93   357.4  845.31   377.2  829.25
     407   802.8   456.6  757.06   466.6  749.09   476.5  744.34   496.4  742.88
   506.3  739.74   526.2  730.51   538.5  728.46     546   728.2   553.5  728.48
   565.8  730.28   585.7  737.37   595.6  738.68     685  742.22   804.1  743.77
  1012.6  742.28  1022.5  742.87  1032.4  745.28  1052.3   753.7    1092  768.34
#Mann= 3 , 0 , 0
       0      .1       0   538.5    .045       0   553.5      .1       0
Bank Sta=538.5,553.5
XS Rating Curve= 0 ,0
Exp/Cntr=0.3,0.1

Type RM Length L Ch R = 1 ,8916.7  ,291.6,300,308.5
XS GIS Cut Line= 3
     1910932.116      455325.095     1910887.303      454780.937
      1910842.49      454236.779
#Sta/Elev= 30
       0  980.36    29.8  965.81    59.6  952.72   158.8  914.93   228.3  887.22
     278  863.77   387.2  808.87     407  797.02     417  789.09   426.9  778.31
   446.7  750.98   456.6  742.39   466.6  740.09   496.4  740.61   506.3  738.44
   526.2  728.59   538.5  726.48     546   726.4   553.5  726.52   565.8  727.59
   575.8  730.17   595.6  737.08   605.6  739.15   615.5  739.72   853.8  743.17
   923.2  742.74  1032.4  740.02  1042.4  740.95  1052.3  744.15    1092  760.92
#Mann= 3 , 0 , 0
       0      .1       0   538.5    .045       0   553.5      .1       0
Bank Sta=538.5,553.5
XS Rating Curve= 0 ,0
Exp/Cntr=0.3,0.1

Type RM Length L Ch R = 1 ,8616.7  ,302,300,298
XS GIS Cut Line= 3
     1911025.881      455335.065     1911183.474      454810.403
     1911341.797      454288.481
#Sta/Elev= 30
       0  973.38    89.6  922.28   139.4  897.44   209.2  864.23   268.9  834.43
   348.6  787.95   368.5  773.92   398.4  749.65   408.4  742.87   418.3  739.68
   448.2  738.34   488.1  734.44   517.9  727.77   540.3  725.26   555.3  724.57
   557.7  724.47   567.6  724.48   577.6  725.69   597.4  732.76   607.3  735.02
  617.21  735.45   726.3  735.21   875.1  736.35     885  737.16   894.9  741.22
   914.7  753.48   944.5  769.22   984.1  791.28  1053.6  826.31  1093.2  845.43
#Mann= 3 , 0 , 0
       0      .1       0   540.3    .045       0   555.3      .1       0
#XS Ineff= 2 , 0
                          617.17          735.45
Permanent Ineff=
       F       F
Bank Sta=540.3,555.3
XS Rating Curve= 0 ,0
Exp/Cntr=0.3,0.1

Type RM Length L Ch R = 1 ,8316.7  ,240.5,237.9,235.4
XS GIS Cut Line= 3
     1911353.092       455442.94      1911464.54      454908.435
     1911576.395      454374.015
#Sta/Elev= 30
       0  918.03    29.8  898.41    39.7   893.6     139  851.56   188.6   837.6
   307.8  793.49   337.5  784.46   367.3   776.7   387.2  772.79     417   770.8
   426.9  768.93   436.8  764.26   456.6   748.3   466.6  742.88   486.4  740.97
   496.4  737.98   516.2  727.16   526.2   723.8   538.5  722.42     546  722.23
   553.5  722.52   565.8  724.48   585.7  731.45   595.6  732.84     824  733.37
   843.8  734.98   853.8  739.52     953  799.82  1022.5  845.98    1092   885.2
#Mann= 3 , 0 , 0
       0      .1       0   538.5    .045       0   553.5      .1       0
#XS Ineff= 2 , 0
                          764.17          733.57
Permanent Ineff=
       F       F
Bank Sta=538.5,553.5
XS Rating Curve= 0 ,0
Exp/Cntr=0.3,0.1

Type RM Length L Ch R = 1 ,8078.7  ,355.3,358.8,362.2
XS GIS Cut Line= 4
     1911666.334      455502.918     1911698.395      454957.864
     1911719.212      454739.024     1911795.681       454455.56
#Sta/Elev= 30
       0  877.41    69.5  842.02   109.2  824.11   148.9  809.18   188.6  792.09
   258.1   764.6     278  760.81   337.5  758.46   416.9  753.24   436.8  750.97
   496.4  738.14   526.1  735.28   536.1  732.57     546  727.96   558.9   723.5
     566  722.15   573.9  721.91     576  721.85   615.9  727.41   635.9  728.93
   745.8  730.64   755.8  732.69   765.8  737.55   785.4  751.86   795.2  757.87
   844.1  782.27   863.7  793.28   902.8  818.74   971.3   865.6  1059.4  922.18
#Mann= 3 , 0 , 0
       0      .1       0   558.9    .045       0   573.9      .1       0
Bank Sta=558.9,573.9
XS Rating Curve= 0 ,0
Exp/Cntr=0.3,0.1

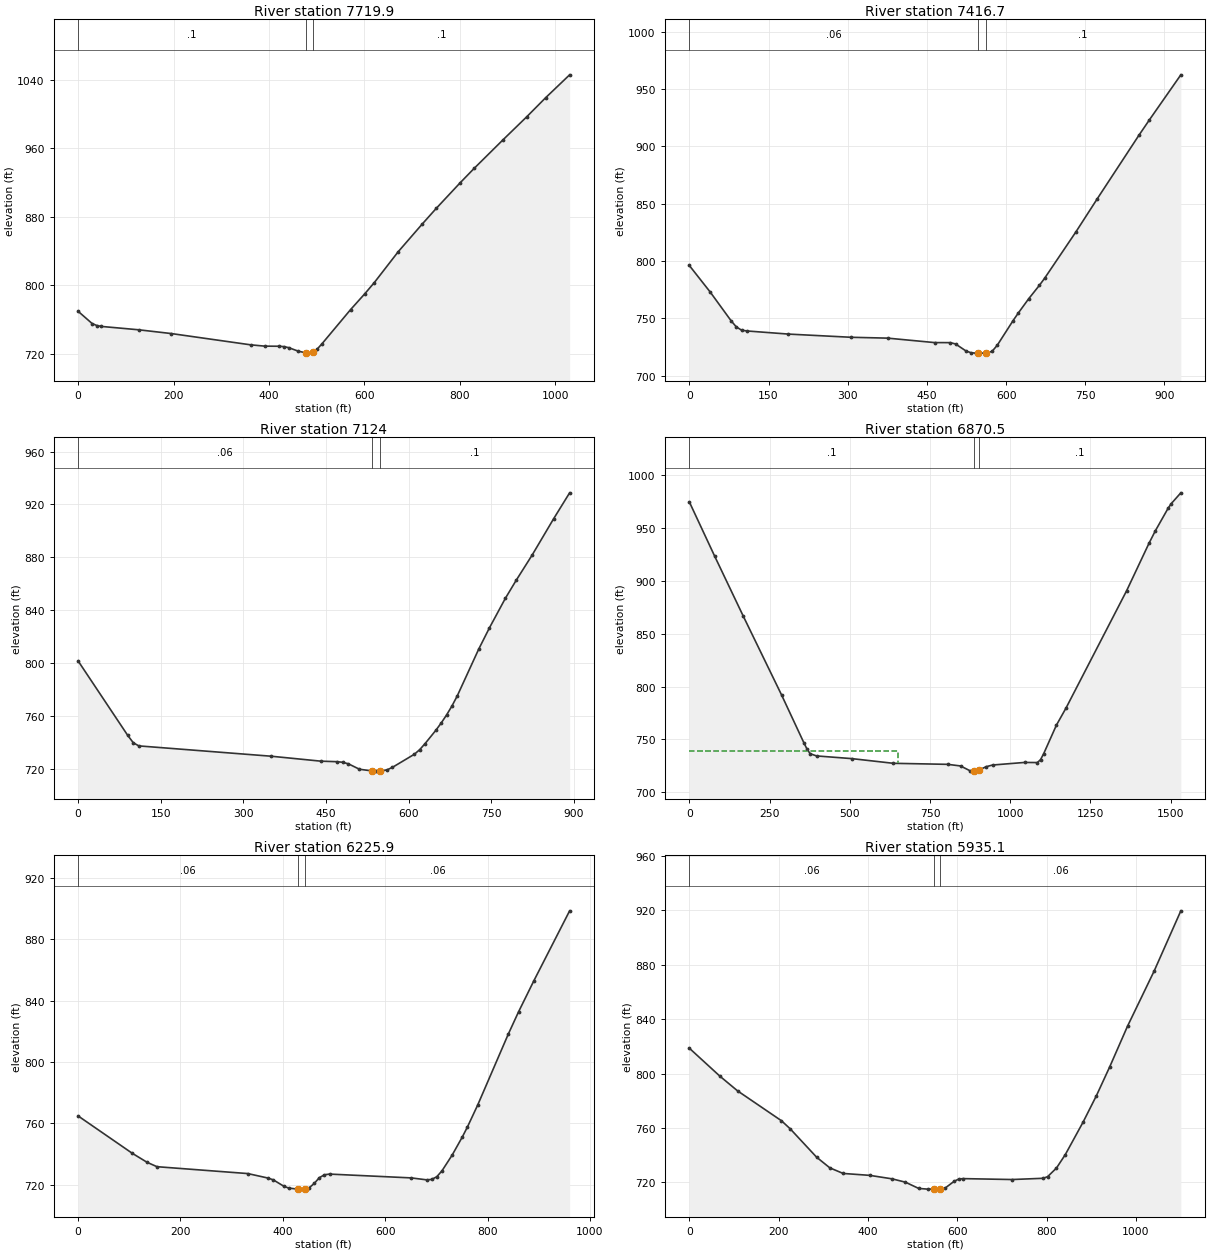
Type RM Length L Ch R = 1 ,7719.9  ,302.5,303.3,303
XS GIS Cut Line= 3
      1911761.76      455335.498     1912025.143      455088.078
     1912189.273      454439.614
#Sta/Elev= 30
       0  769.35    29.3  755.07    39.1  752.74    48.8  751.66     127  747.73
   195.3  743.33   361.4  730.18   391.3  728.62   421.3  728.51   431.3  728.06
   441.2  726.89   461.2  722.81   477.3  720.78   481.2  720.46   491.2  721.22
   492.3  721.65   501.1  725.12   511.1  731.31     571  771.23     601  789.87
     621  802.98   670.9  838.91   720.8  870.96   750.7   889.6   800.6  919.37
   830.6  936.59   890.5  969.64   940.4  996.65   980.4 1019.12  1030.3 1045.67
#Mann= 3 , 0 , 0
       0      .1       0   477.3    .045       0   492.3      .1       0
Bank Sta=477.3,492.3
XS Rating Curve= 0 ,0
Exp/Cntr=0.3,0.1

Type RM Length L Ch R = 1 ,7416.7  ,292,292.6,294.3
XS GIS Cut Line= 3
     1912174.793      455626.816     1912329.798      455095.305
     1912420.218      454728.919
#Sta/Elev= 30
       0     796    39.6  772.81    79.1  747.78      89  742.42    98.9   739.6
   108.8   738.9   187.8  736.16   306.5  733.37   375.7  732.63   464.7  728.74
   494.3  728.71   504.2  727.56     524  721.44   533.9  719.84   543.8  719.55
   546.2  719.56   561.2  719.68   563.6  719.71   573.5   721.1   583.4  726.52
   613.2  747.89   623.2  754.59     643   767.1   662.9  778.59   672.8  784.74
   732.4  825.42   772.1  853.78   851.6  909.61   871.4  923.01     931  962.33
#Mann= 3 , 0 , 0
       0     .06       0   546.2    .045       0   561.2      .1       0
Bank Sta=546.2,561.2
XS Rating Curve= 0 ,0
Exp/Cntr=0.3,0.1

Type RM Length L Ch R = 1 ,7124    ,259,253.5,248.1
XS GIS Cut Line= 3
     1912432.821      455730.575     1912613.764      455157.914
     1912621.746      454866.597
#Sta/Elev= 30
       0  801.61    90.1  745.26   100.1  739.75   110.1  737.36   350.3  729.55
   440.4  725.81   470.4   725.4   480.4  724.93   490.5   723.8   510.5  719.71
   533.3  718.41   540.5  718.27   548.3  718.36   560.5   719.2   570.5  721.15
   610.3  731.06     620  734.55   629.7  739.11   649.1   749.1   658.8   754.6
   668.6  760.69   678.3  767.44     688  775.11   726.8  810.36   746.3  826.51
   775.4     849   794.8  862.46     824  881.72   862.8  909.04     892  928.77
#Mann= 3 , 0 , 0
       0     .06       0   533.3    .045       0   548.3      .1       0
Bank Sta=533.3,548.3
XS Rating Curve= 0 ,0
Exp/Cntr=0.3,0.1

Type RM Length L Ch R = 1 ,6870.5  ,669.3,644.6,619.9
XS GIS Cut Line= 4
     1912684.931      456154.912     1912804.929      455798.088
     1912849.878       455101.38     1912753.653        454654.4
#Sta/Elev= 30
       0  974.53    79.2  923.09   168.4  866.36   287.3  792.18   356.6  747.14
   366.6  740.99   376.5  736.58   396.4  734.46   506.1  731.92   635.8  727.48
   805.3   726.5   845.2  724.98   875.1  720.39   885.1  720.09   886.6  720.16
   901.6     721     925  724.26     945  725.86  1044.7   728.3  1084.6  728.19
  1094.5  730.91  1104.4  736.61  1144.2  763.65    1174  779.74  1362.9   890.6
  1432.4  935.31  1452.3  947.18  1492.1  968.51    1502  972.92  1531.8   983.1
#Mann= 3 , 0 , 0
       0      .1       0   886.6    .045       0   901.6      .1       0
#XS Ineff= 2 , 0
          650.68  739.24
Permanent Ineff=
       F       F
Bank Sta=886.6,901.6
XS Rating Curve= 0 ,0
Exp/Cntr=0.3,0.1

Type RM Length L Ch R = 1 ,6225.9  ,293.6,290.7,287.8
XS GIS Cut Line= 3
     1913727.821       455098.72     1913520.307      455056.153
     1912882.343      454664.809
#Sta/Elev= 30
       0  764.92   105.9  740.57   134.8  734.71   154.1  731.86   331.6  727.38
   371.5  724.42   381.5  723.26   401.4  719.24   411.4  717.92   428.8  717.28
   431.4  717.25   443.8  717.49   451.3  718.05   461.3  720.97   471.3  724.71
   481.3   726.6   491.2  727.05   650.9  724.56   680.8   723.3   690.8  723.56
   700.8  725.34   710.8  729.13   730.8  739.43   750.7  751.26   760.7  757.78
   780.6  771.96   840.5  818.25   860.5  832.73   890.4  852.95   960.3  898.53
#Mann= 3 , 0 , 0
       0     .06       0   428.8    .045       0   443.8     .06       0
Bank Sta=428.8,443.8
XS Rating Curve= 0 ,0
Exp/Cntr=0.3,0.1

Type RM Length L Ch R = 1 ,5935.1  ,534,530.8,527.7
XS GIS Cut Line= 3
     1913940.656      454899.187     1913663.971      454771.486
     1912938.191      454444.087
#Sta/Elev= 30
       0  818.69    68.8     798   108.1  787.28   206.4   765.3   226.1  759.32
   285.1  738.49   314.7  730.65   344.5  726.54   404.3  725.12     454  722.57
   483.9  720.12   513.7  715.52   533.6     715   547.1  715.02   562.1  715.02
   573.4  715.89   593.4  720.81   603.3  722.38   613.3  722.73   722.7  722.06
   792.4  722.97   802.4  724.15   822.3   730.5   842.2  740.45     882  764.34
   911.8  783.75   941.7  805.04   981.5   834.9  1041.2  875.52  1100.9  919.75
#Mann= 3 , 0 , 0
       0     .06       0   547.1    .045       0   562.1     .06       0
Bank Sta=547.1,562.1
XS Rating Curve= 0 ,0
Exp/Cntr=0.3,0.1

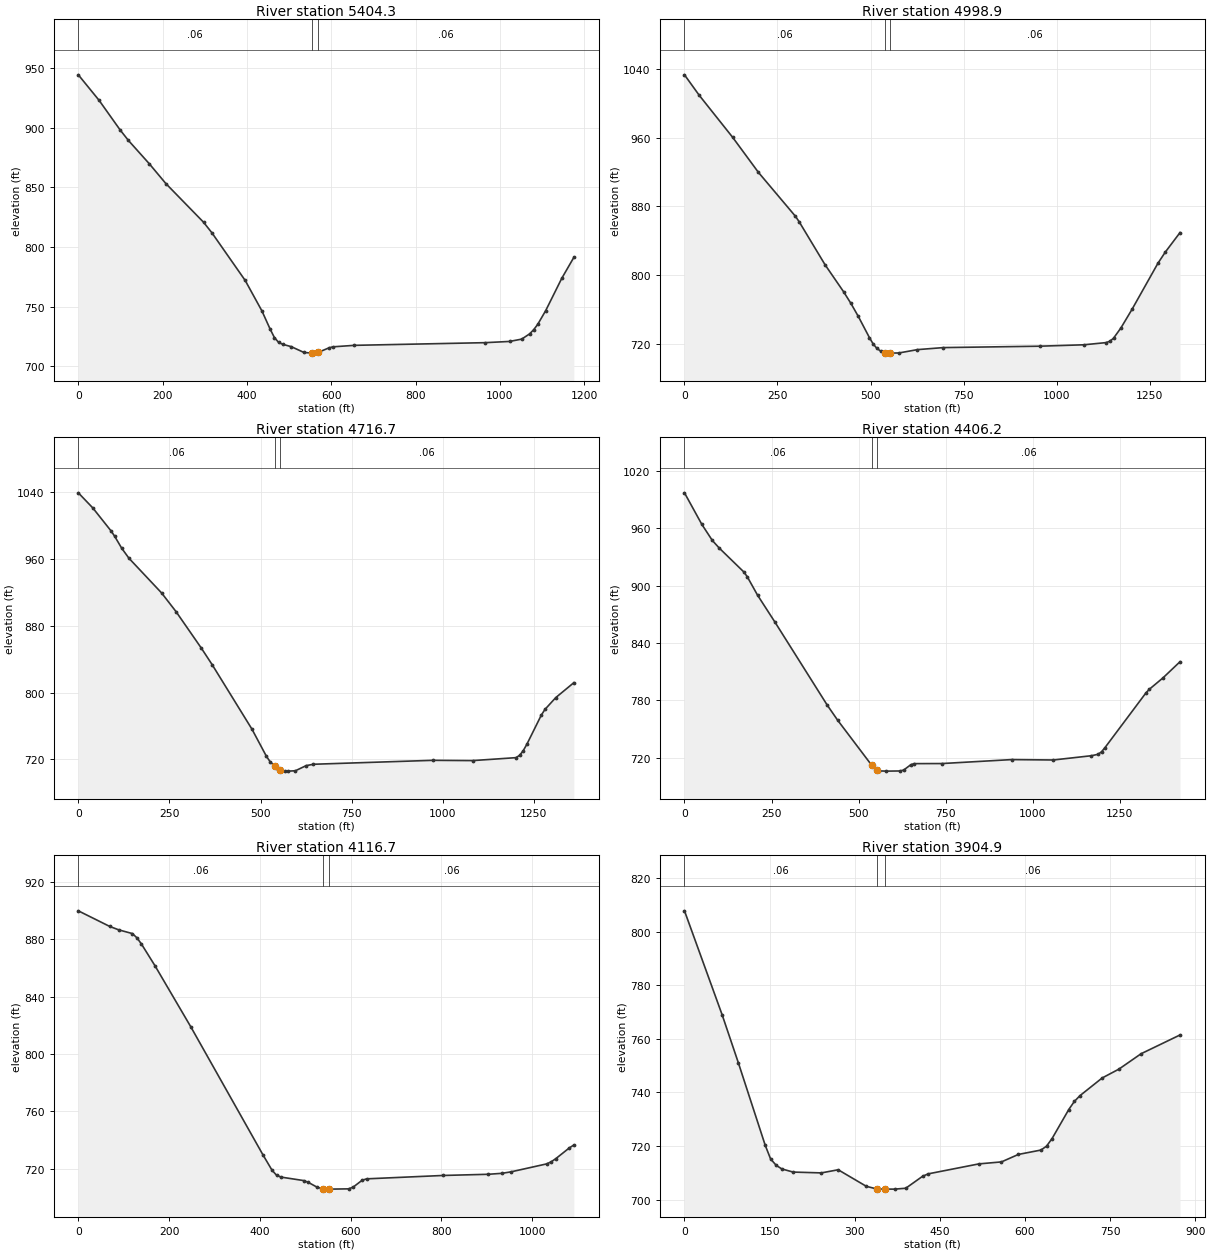
Type RM Length L Ch R = 1 ,5404.3  ,416.1,405.4,394.6
XS GIS Cut Line= 4
     1914224.865       454228.17     1913759.746      454218.116
     1913251.604      454069.132     1913070.694      454066.471
#Sta/Elev= 30
       0  944.61    49.5  923.09      99  898.42   118.8  889.53   168.3  869.97
   207.9  853.22     297  820.87   316.8  812.03   395.9  771.95   435.5  746.43
   455.3  730.92   465.2  724.03   475.2  719.93   485.2   718.3   505.2  716.35
   535.2   711.5   554.5  710.92   569.5  711.59   595.1  715.42   605.1  716.24
   655.1  717.46   964.8   719.7  1023.3  720.74  1051.9  722.68  1070.9  727.14
  1080.5  730.65    1090   735.1    1109  746.71  1147.1  773.82  1175.7  791.35
#Mann= 3 , 0 , 0
       0     .06       0   554.5    .045       0   569.5     .06       0
Bank Sta=554.5,569.5
XS Rating Curve= 0 ,0
Exp/Cntr=0.3,0.1

Type RM Length L Ch R = 1 ,4998.9  ,286.1,282.2,277.4
XS GIS Cut Line= 3
     1914223.167      453685.923     1913139.865      453896.203
     1912919.049      453954.733
#Sta/Elev= 30
       0 1033.13    39.8 1009.22   129.2  960.58   198.8  919.62   298.2   868.6
   308.2  862.25   377.8  812.23   427.5  780.89   447.4   767.2   467.3  752.03
   497.1  727.45     507  720.15     517  714.98   526.9  711.84   538.7  709.86
   546.8  709.38   553.7  709.39   576.6  709.59   626.3  713.46   695.9  715.82
   954.4  717.44  1073.7  719.08  1133.3  721.62  1143.2  723.19  1153.2   726.7
    1173  738.63  1202.8   760.2  1272.4  813.78  1292.2   826.8    1332  849.64
#Mann= 3 , 0 , 0
       0     .06       0   538.7    .045       0   553.7     .06       0
Bank Sta=538.7,553.7
XS Rating Curve= 0 ,0
Exp/Cntr=0.3,0.1

Type RM Length L Ch R = 1 ,4716.7  ,318.5,310.5,303.4
XS GIS Cut Line= 3
     1914119.902      453325.531     1913609.394      453519.173
      1912860.52      453837.674
#Sta/Elev= 30
       0 1038.91    39.7 1020.86    89.4  993.56    99.3  987.24   119.1   972.6
     139  960.61   228.3  919.22     268  896.87   337.5  853.14   367.3  833.29
   476.5  756.12   516.2  723.64   526.1  717.32   538.5   712.2   553.5  707.66
   565.8  706.07   575.8  705.94   595.6  706.37   625.4  712.55   645.2  714.16
   972.7  718.86  1081.9  718.53    1201  722.06  1210.9  724.83  1220.8  730.36
  1230.8  738.08  1270.5  772.98  1280.4  779.75  1310.2  793.94  1359.8  811.79
#Mann= 3 , 0 , 0
       0     .06       0   538.5    .045       0   553.5     .06       0
Bank Sta=538.5,553.5
XS Rating Curve= 0 ,0
Exp/Cntr=0.3,0.1

Type RM Length L Ch R = 1 ,4406.2  ,294.2,289.5,284.8
XS GIS Cut Line= 3
     1913871.424      452890.099     1913020.146       453632.82
      1912738.14      453715.294
#Sta/Elev= 30
       0  997.16      50  964.02      80  947.28     100  939.26     170  914.48
     180  909.52     210  889.94   259.9  861.76   409.9  774.95   439.9  759.11
   537.3  712.14   549.9  707.23   552.3  706.93   559.9  705.98   579.9  705.73
   619.9  705.91   629.8  706.89   649.8  712.34   659.8  713.58   739.8  713.67
   939.8  717.81  1059.8   717.4  1168.9  721.86  1188.5  723.38  1198.3  726.08
  1208.1   730.4  1325.6  787.63  1335.4  791.44  1374.6  803.38  1423.6  820.32
#Mann= 3 , 0 , 0
       0     .06       0   537.3    .045       0   552.3     .06       0
Bank Sta=537.3,552.3
XS Rating Curve= 0 ,0
Exp/Cntr=0.3,0.1

Type RM Length L Ch R = 1 ,4116.7  ,209.8,211.8,213.8
XS GIS Cut Line= 3
     1913566.893      452626.598     1913239.293      453063.398
     1912911.693      453500.198
#Sta/Elev= 30
       0     900    69.5  889.06    89.4  886.69   119.1  884.12     129  881.22
     139  876.88   168.8  861.74   248.2  818.85     407  729.58   426.9  718.91
   436.8  715.44   446.7  714.13   496.4  711.71   506.3  710.53   526.2  707.07
   538.5  705.93   553.5  705.73   595.6  705.92   605.6  707.13   625.4  711.92
   635.4  712.91   804.1  715.27   903.4  716.09   933.2  716.76     953  717.76
  1032.4  723.37  1042.4  724.89  1052.3  727.03  1082.1  734.53    1092  736.55
#Mann= 3 , 0 , 0
       0     .06       0   538.5    .045       0   553.5     .06       0
Bank Sta=538.5,553.5
XS Rating Curve= 0 ,0
Exp/Cntr=0.3,0.1

Type RM Length L Ch R = 1 ,3904.9  ,415.3,428,440.7
XS GIS Cut Line= 4
     1913344.719      452768.179     1913195.734      452797.444
     1912870.995      453159.387     1912642.364      453215.132
#Sta/Elev= 30
       0  807.85    66.4     769    94.9  751.12   142.3  720.29   151.8  715.17
   161.8  712.77   171.7  711.44   191.5  710.28   241.2  709.97   270.9  711.14
   320.5  704.96     339  703.97     354  703.92   370.2  703.91     390  704.24
   419.8  708.73   429.7  709.62     519  713.34   558.7  714.08   588.5  716.87
   628.2   718.5   638.1  719.95   647.9  722.81   677.3  733.64   687.1  736.65
   696.9   738.8   736.2  745.43   765.6  748.72   804.8  754.48   873.4  761.49
#Mann= 3 , 0 , 0
       0     .06       0     339    .045       0     354     .06       0
Bank Sta=339,354
XS Rating Curve= 0 ,0
Exp/Cntr=0.3,0.1

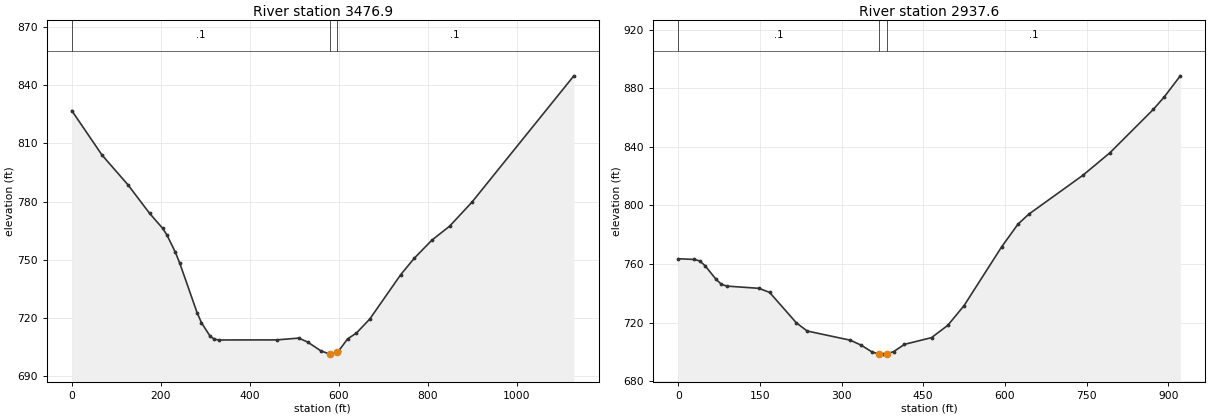
Type RM Length L Ch R = 1 ,3476.9  ,525.4,539.3,553.3
XS GIS Cut Line= 3
     1913401.134      452459.928     1913099.959      452536.722
     1912312.582      452758.383
#Sta/Elev= 30
       0  826.91      68  803.98   126.3  788.64   174.8  773.99     204  766.28
   213.7  762.88   233.1  753.78   242.8  748.21   281.7  722.75   291.4  717.61
   310.8  710.63   320.8  709.01   330.8  708.63   460.4  708.67   510.3  709.59
   530.3  707.55   560.2     703   580.2  701.33   580.5  701.33   595.5  702.29
   600.1  702.99     620  709.16     640  712.21   669.9  719.41   739.8  742.37
   769.7  750.69   809.6  760.09   849.5  767.31   899.4  779.61  1128.8  844.83
#Mann= 3 , 0 , 0
       0      .1       0   580.5    .045       0   595.5      .1       0
Bank Sta=580.5,595.5
XS Rating Curve= 0 ,0
Exp/Cntr=0.3,0.1

Type RM Length L Ch R = 1 ,2937.6  ,311.7,320.9,330.1
XS GIS Cut Line= 3
      1913230.32      452273.339     1912990.881      452116.373
     1912392.073      451902.327
#Sta/Elev= 30
       0  763.57    29.6  763.11    39.5  762.08    49.4   758.8    69.1   749.7
      79  746.24    88.8  744.92   148.1   743.4   167.8  740.61   217.2  719.76
   236.9  714.25   316.1  707.98     336   704.6   355.9  699.98   368.8  698.55
   375.7  698.48   383.8  698.85   395.6  700.17   415.5  705.15   465.2  709.74
     495   718.1   524.8  731.48   594.3  771.86   624.1  787.23     644  794.03
   743.4  820.59     793  835.95   872.5  865.46   892.4  873.89   922.2  888.43
#Mann= 3 , 0 , 0
       0      .1       0   368.8    .045       0   383.8      .1       0
Bank Sta=368.8,383.8
XS Rating Curve= 0 ,0
Exp/Cntr=0.3,0.1