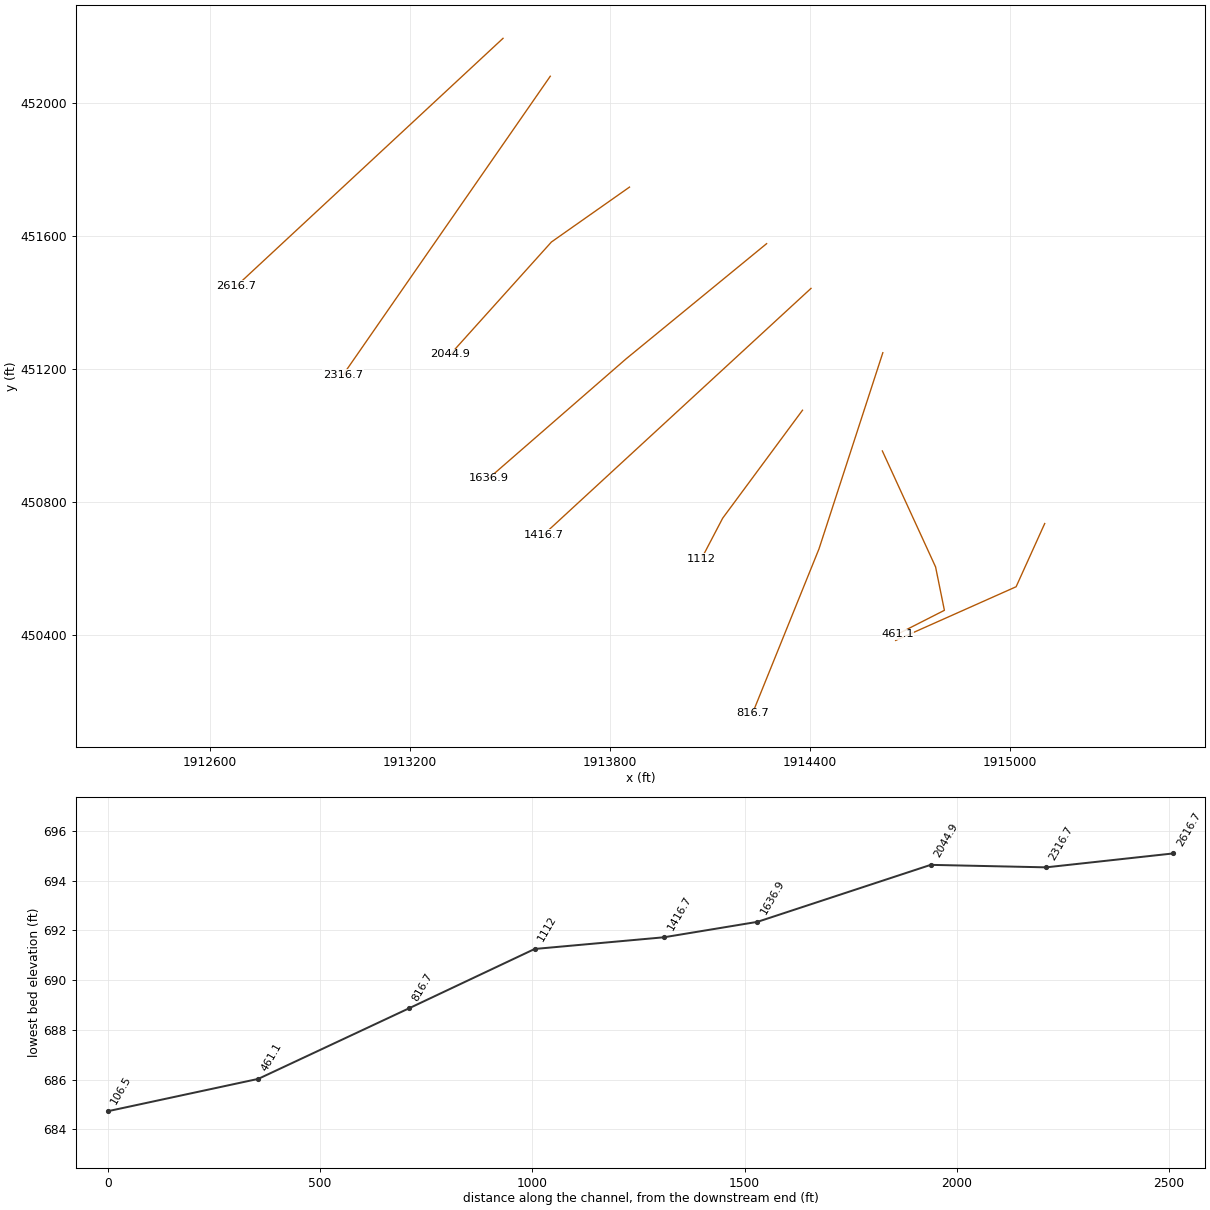
HEC-RAS study BellsCreek.prj: BellsCreek

--- BellsCreek.g01 (geometry) --- (continued)

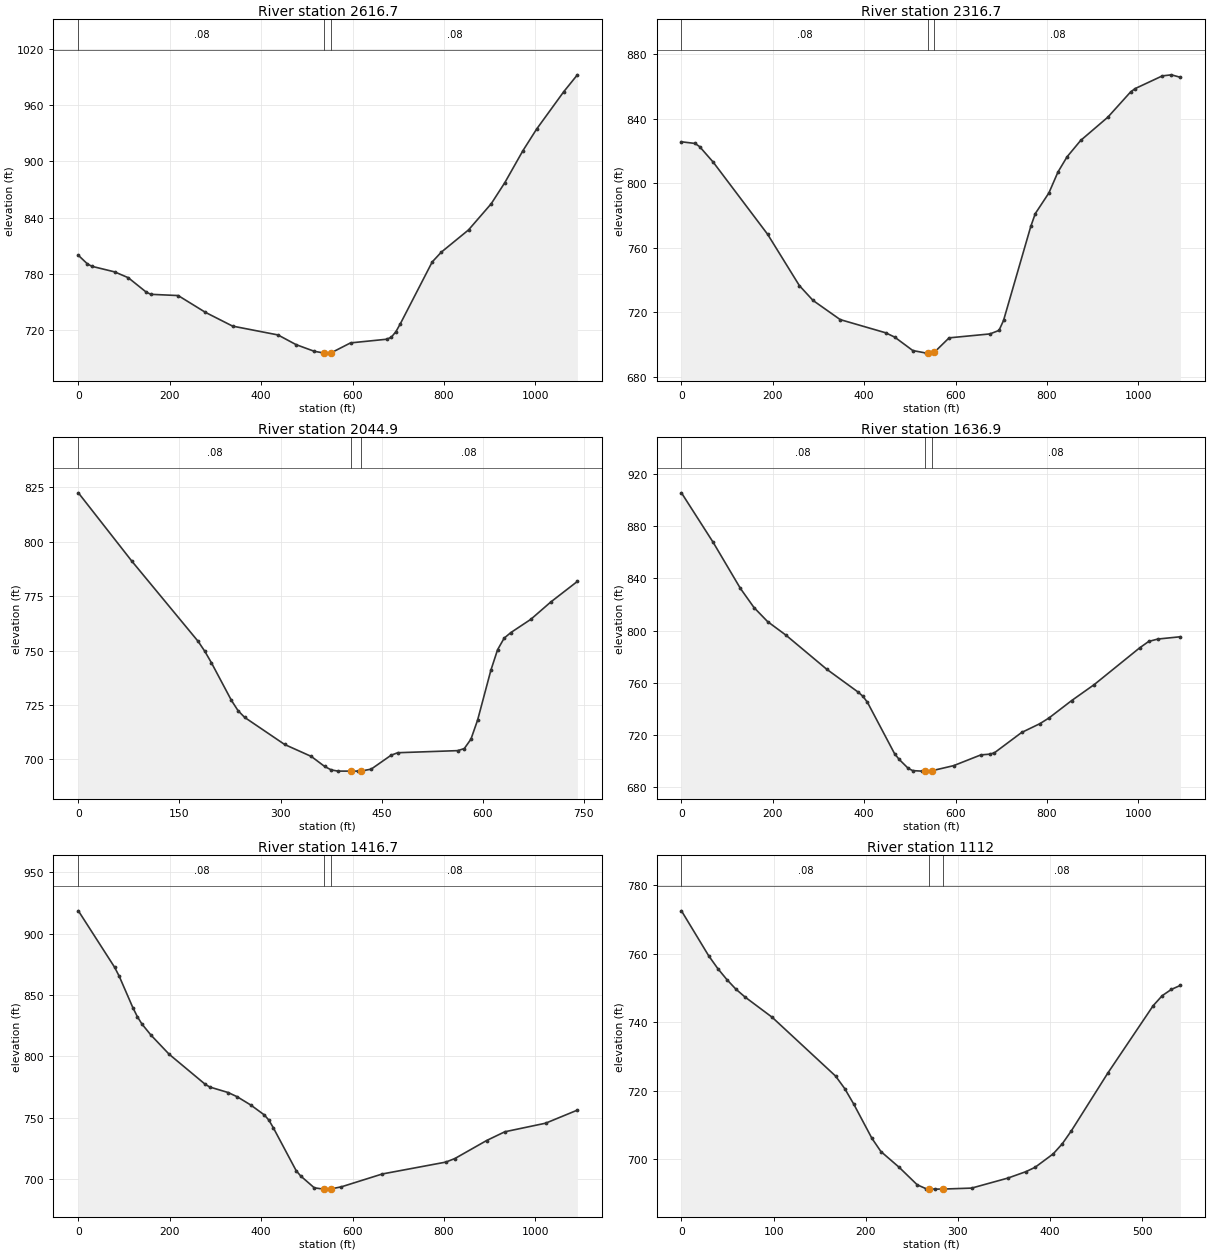
Type RM Length L Ch R = 1 ,2616.7  ,295.1,300,304.9
XS GIS Cut Line= 3
     1913478.954       452193.62      1913079.34      451821.565
     1912679.726       451449.51
#Sta/Elev= 30
       0  799.67    19.8  790.48    29.8  787.88    79.4  781.95   109.2  775.73
   148.9  760.16   158.8  757.96   218.4  756.64     278  738.71   337.5  723.98
   436.8  714.54   476.5  704.16   516.2  697.06   538.5  695.13     546  695.09
   553.5  695.51   595.6  706.03     675  709.96     685   712.2   694.9  718.03
   704.8  726.69   774.3  792.57   794.2  803.04   853.8  826.82   903.4  854.77
   933.2  877.35   972.9  911.61  1002.6  934.48  1062.2  974.61    1092  992.64
#Mann= 3 , 0 , 0
       0     .08       0   538.5    .045       0   553.5     .08       0
Bank Sta=538.5,553.5
XS Rating Curve= 0 ,0
Exp/Cntr=0.3,0.1

Type RM Length L Ch R = 1 ,2316.7  ,274.7,271.7,268.7
XS GIS Cut Line= 3
     1913620.646      452079.721     1913309.856      451630.805
     1912999.067      451181.888
#Sta/Elev= 30
       0  825.72    29.8  824.69    39.7  822.73    69.5  813.08   188.6  768.29
   258.1  736.42   287.9  727.24   347.4  715.34   446.7  707.17   466.6  704.48
   506.3  696.13   536.1  694.53   538.5  694.54   553.5   695.1   585.7  704.01
     675  706.45   694.9  708.64   704.8  714.79   764.4  773.15   774.3  781.15
   804.1  793.98     824     807   843.8  816.38   873.6  826.56   933.2  841.03
   982.8  856.64   992.7  858.73  1052.3  866.63  1072.2  867.29    1092  865.73
#Mann= 3 , 0 , 0
       0     .08       0   538.5    .045       0   553.5     .08       0
Bank Sta=538.5,553.5
XS Rating Curve= 0 ,0
Exp/Cntr=0.3,0.1

Type RM Length L Ch R = 1 ,2044.9  ,411.4,408.1,405.3
XS GIS Cut Line= 3
     1913858.182      451746.573     1913624.064      451581.626
     1913320.775      451243.751
#Sta/Elev= 30
       0  822.42      79  791.18   177.8  754.18   187.6  749.66   197.5  744.35
   227.1  727.12     237  722.37   246.9  719.27   306.1  706.86   345.6  701.38
   365.4  696.78   375.2  695.19   385.1  694.64   404.1  694.64   414.7  694.63
   419.1  694.67   434.4  695.53     464  701.93   473.9  703.08   562.8  704.04
   572.6  704.98   582.5  709.32   592.4  718.11   612.1     741     622  750.38
   631.8  755.71   641.7  758.25   671.3  764.33   700.9  772.28   740.4  781.74
#Mann= 3 , 0 , 0
       0     .08       0   404.1    .045       0   419.1     .08       0
Bank Sta=404.1,419.1
XS Rating Curve= 0 ,0
Exp/Cntr=0.3,0.1

Type RM Length L Ch R = 1 ,1636.9  ,218.9,220.2,221
XS GIS Cut Line= 3
     1914269.334      451576.625     1913847.465      451230.089
     1913435.727       450871.06
#Sta/Elev= 30
       0  905.51    69.5  867.52     129  832.31   158.8  817.63   188.6  806.86
   228.3   796.6   317.6  770.48   387.1  752.78     397  749.71     407   745.1
   466.5  705.68   476.5  701.33   496.3  694.48   506.2  692.73   526.1  692.34
   532.4  692.34   547.4  692.58   595.6  696.52   655.2  704.76   675.1  705.35
     685  706.38   744.6  721.95   784.3  728.65   804.2     733   853.9  746.35
   903.5  758.64  1002.8  786.74  1022.7  791.67  1042.6  793.51  1092.2  795.27
#Mann= 3 , 0 , 0
       0     .08       0   532.4    .045       0   547.4     .08       0
Bank Sta=532.4,547.4
XS Rating Curve= 0 ,0
Exp/Cntr=0.3,0.1

Type RM Length L Ch R = 1 ,1416.7  ,300.2,304.6,309
XS GIS Cut Line= 3
      1914402.45      451442.242     1914001.247      451071.901
     1913600.045       450701.56
#Sta/Elev= 30
       0  918.68    79.4   872.6    89.4  865.34   119.1  839.83     129  832.43
     139  826.42   158.8  817.36   198.6  801.74     278  777.08   287.9  774.95
   327.6  770.52   347.4  767.08   377.2  760.34     407  752.21     417  747.94
   426.9  741.59   476.5  706.86   486.4  702.48   516.2  692.81   536.1  691.72
   538.5  691.74   553.5  691.95   575.8  693.62   665.1  704.08   804.1  713.76
     824  716.68   893.4  731.36   933.2  738.49  1022.5  745.49    1092  756.16
#Mann= 3 , 0 , 0
       0     .08       0   538.5    .045       0   553.5     .08       0
Bank Sta=538.5,553.5
XS Rating Curve= 0 ,0
Exp/Cntr=0.3,0.1

Type RM Length L Ch R = 1 ,1112    ,288.2,295.4,301
XS GIS Cut Line= 3
     1914376.967      451076.143     1914137.528       450751.57
     1914073.678       450629.19
#Sta/Elev= 30
       0  772.54    29.5  759.43    39.4  755.68    49.2  752.48      59  749.68
    68.9  747.38    98.4  741.45   167.2  724.28   177.1  720.63   186.9   716.1
   206.6  706.11   216.4  702.23   236.1  697.65   255.8  692.51   265.6  691.35
     269  691.32   275.4  691.25     284  691.27   314.8  691.55   354.2  694.48
   373.8  696.36   383.7  697.63   403.3  701.54   413.2   704.5     423  708.27
   462.5  725.12   511.8  744.84   521.6  747.76   531.5  749.58   541.4  750.77
#Mann= 3 , 0 , 0
       0     .08       0     269    .045       0     284     .08       0
Bank Sta=269,284
XS Rating Curve= 0 ,0
Exp/Cntr=0.3,0.1

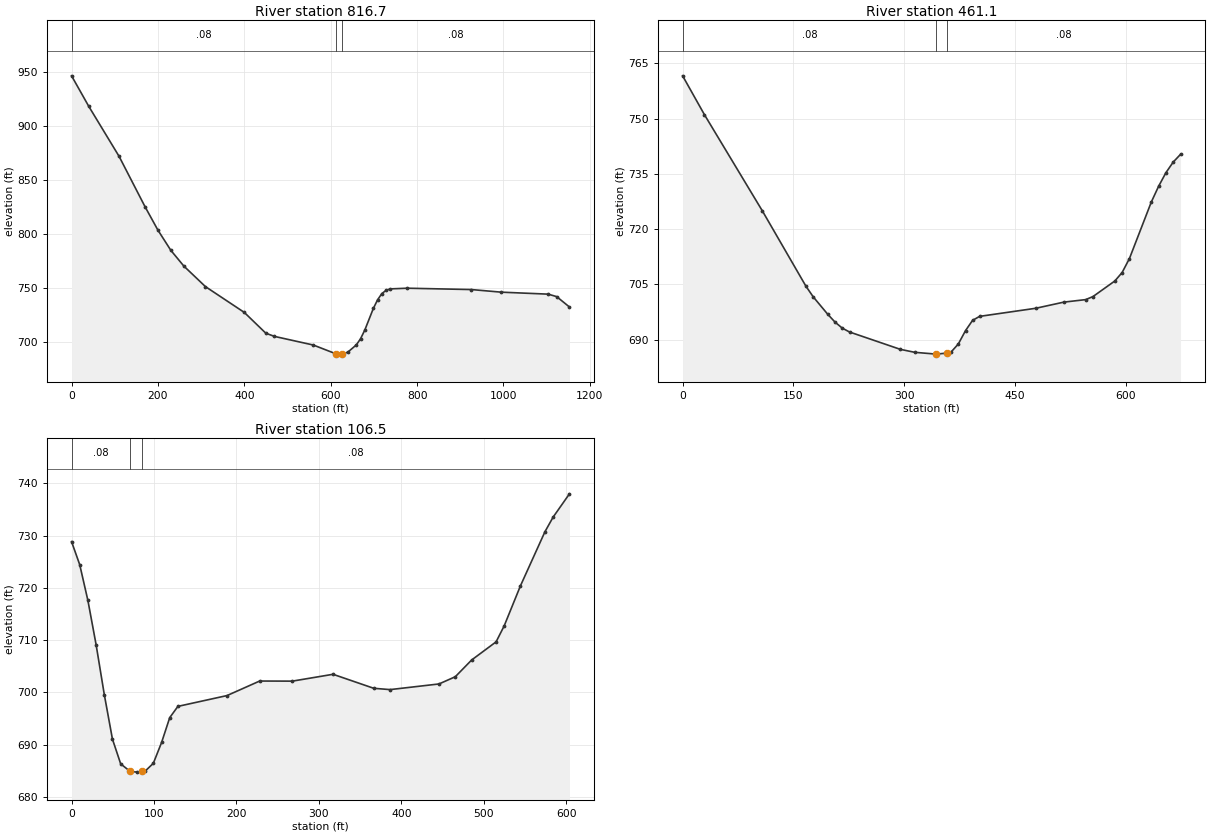
Type RM Length L Ch R = 1 ,816.7   ,338.7,355.6,374
XS GIS Cut Line= 3
     1914617.834      451248.904     1914426.421      450659.427
     1914226.982      450165.167
#Sta/Elev= 30
       0  946.33      40  917.98     110  871.85   169.9   825.4   199.9  803.61
   229.9  784.87   259.9  770.36   309.9  751.36   399.9  727.47   449.8  708.22
   469.8  705.27   559.8  697.28   612.3  689.12   619.8  688.87   627.3  689.11
   639.5  690.65   659.3   697.4   669.1  703.08     679  711.19   698.7  731.11
   708.6  739.17   718.5  744.93   728.4   747.9   738.2  749.23   777.7  749.85
   925.8   748.6   994.8   746.2  1103.4  744.36  1123.2  742.07  1152.8  732.45
#Mann= 3 , 0 , 0
       0     .08       0   612.3    .045       0   627.3     .08       0
Bank Sta=612.3,627.3
XS Rating Curve= 0 ,0
Exp/Cntr=0.3,0.1

Type RM Length L Ch R = 1 ,461.1   ,373.9,354.5,335.1
XS GIS Cut Line= 4
     1914616.406      450953.763     1914776.032      450605.246
     1914802.464       450474.85     1914661.634      450403.053
#Sta/Elev= 30
       0   761.6    29.5  751.07   108.1   724.9   167.1  704.46   176.9  701.59
   196.6  696.85   206.4  694.74   216.2   693.1   226.1  692.04   294.9  687.33
   314.5  686.52   343.7  686.03   358.7  686.33   363.7   686.6   373.5  688.79
   383.3  692.43   392.8   695.2   402.3  696.28   478.4  698.48   516.4  700.15
     546  700.83   555.9  701.66   585.5  705.89   595.4  708.19   605.3  711.99
   634.9  727.32   644.8   731.6   654.7  735.29   664.6  738.18   674.5  740.28
#Mann= 3 , 0 , 0
       0     .08       0   343.7    .045       0   358.7     .08       0
Bank Sta=343.7,358.7
XS Rating Curve= 0 ,0
Exp/Cntr=0.3,0.1

Type RM Length L Ch R = 1 ,106.5   ,101.4,106.5,111.5
XS GIS Cut Line= 3
     1915103.266      450735.608     1915017.485      450545.655
     1914656.313       450384.43
#Sta/Elev= 30
       0  728.83     9.9  724.42    19.8  717.59    29.8  709.09    39.7  699.58
    49.6  691.04    59.6  686.31    70.8   684.9    79.4  684.73    85.8  684.86
    89.3  684.93    99.2  686.42   109.2   690.4   119.1  695.16     129  697.31
   188.6  699.38   228.2  702.16   267.8  702.14   317.2  703.45   366.6  700.77
   386.4  700.52   445.7   701.6   465.5  702.98   485.3  706.18     515  709.66
   524.8  712.71   544.6   720.4   574.3  730.74   584.2  733.53     604  737.98
#Mann= 3 , 0 , 0
       0     .08       0    70.8    .045       0    85.8     .08       0
Bank Sta=70.8,85.8
XS Rating Curve= 0 ,0
Exp/Cntr=0.3,0.1

Chan Stop Cuts=-1
Use User Specified Reach Order=0
Composite Channel Slope=5